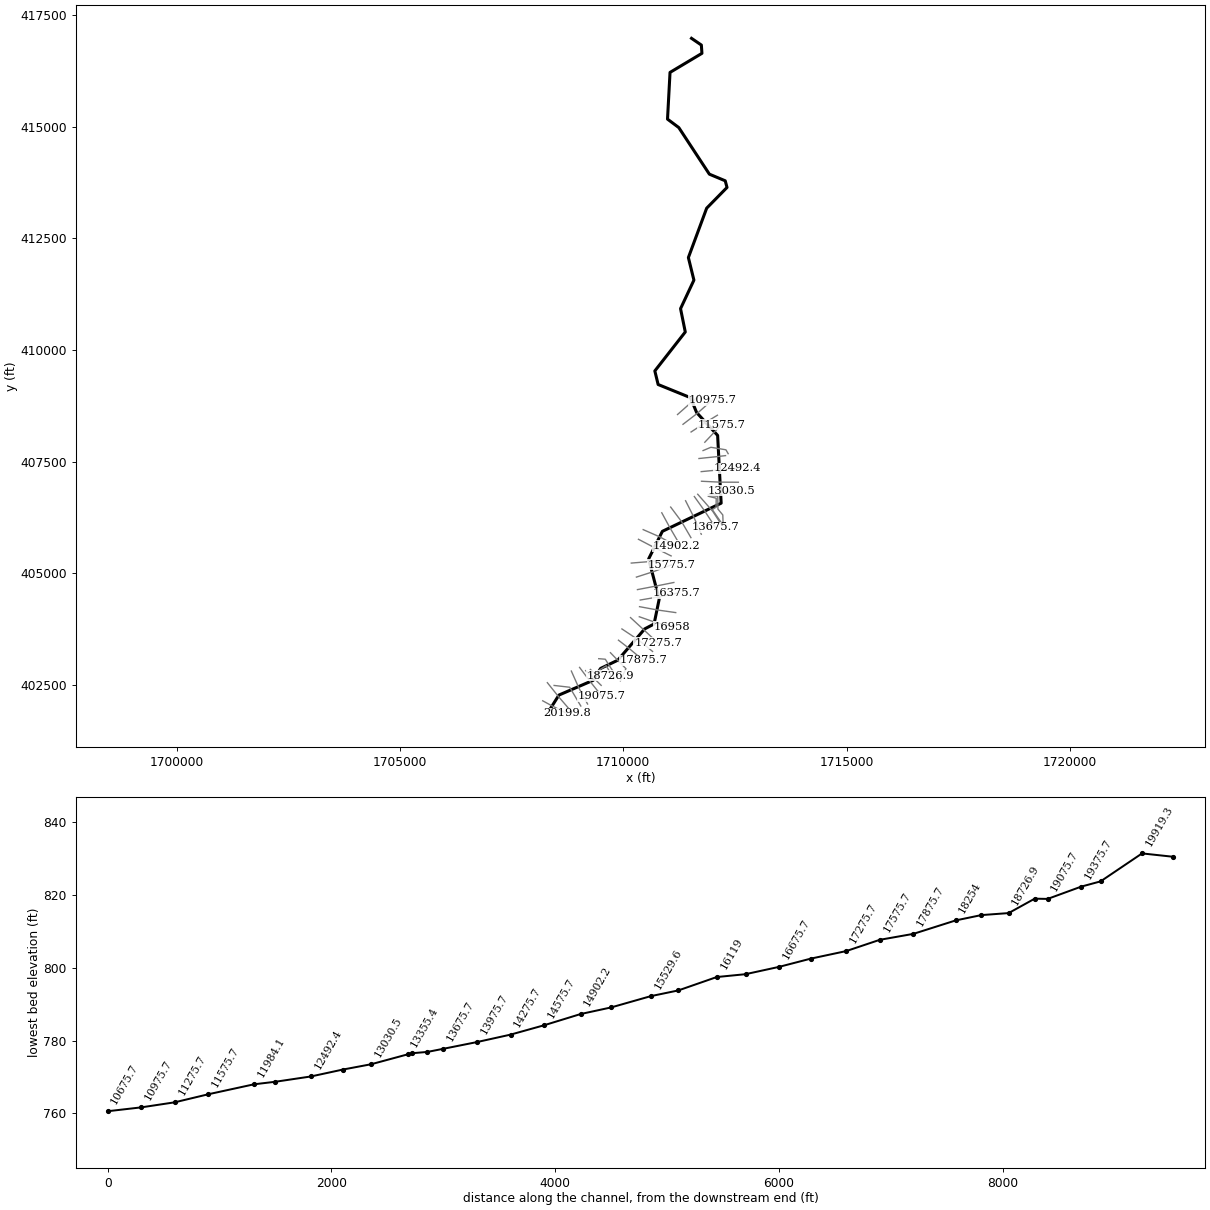
--- BGHORSECK.prj (project) ---

Proj Title=BGHORSECK
Current Plan=p01
Default Exp/Contr=0,0
English Units
Geom File=g01
Flow File=f01
Plan File=p01
BEGIN DESCRIPTION:
END DESCRIPTION:
DSS Export Rating Curves= 0
DSS Export Rating Curve Sorted= 0
DSS Export Volume Flow Curves= 0
DXF OffsetX= 0
DXF OffsetY= 0
DXF ScaleX= 0
DXF ScaleY= 0

--- BGHORSECK.p01 (plan) ---

Plan Title=Floodplain
Program Version=4.00
Geom File=g01
Flow File=f01
K Sum by GR=0
Std Step Tol=0.01
Critical Tol=0.01
Num of Std Step Trials=20
Max Error Tol=0.3
Flow Tol Ratio=0.001
Split Flow NTrial=30
Split Flow Tol=0.02
Split Flow Ratio=0.02
Log Output Level=0
Friction Slope Method=1
Unsteady Friction Slope Method=2
Unsteady Bridges Friction Slope Method=1
Global Log Level=0
CheckData=False
Run HTab=0
Run UNet=0
Run PostProcess=0
UNET Theta=0
UNET Theta Warmup=0
UNET ZTol=0
UNET ZSATol=0
UNET MxIter=0
UNET MaxInSteps=0
UNET DtIC=0
UNET DtMin=0
UNET MaxCRTS=0
UNET WFStab=0
UNET SFStab=0
UNET WFX=0
UNET SFX=0
UNET DSS MLevel=0
UNET DZMax Abort=0
UNET Convert EG Bridges=0
UNET Use Existing IB Tables=0
UNET Froude Limit=0
UNET Froude Power=0
Write IC File=0
Echo Input=False
Echo Output=False
Write Detailed=0

--- BGHORSECK.f01 (steady flow) ---

Flow Title=NFF Regression Equation
Program Version=4.10
Number of Profiles= 1
Profile Names=P100yr
River Rch & RM=BGHORSECK,Main            ,20199.8
 907.746
River Rch & RM=BGHORSECK,Main            ,19075.7
965.4559
River Rch & RM=BGHORSECK,Main            ,17875.7
1344.433
River Rch & RM=BGHORSECK,Main            ,15529.6
1392.557
River Rch & RM=BGHORSECK,Main            ,13975.7
1571.184
River Rch & RM=BGHORSECK,Main            ,12492.4
1771.071
River Rch & RM=BGHORSECK,Main            ,10675.7
1963.943
River Rch & RM=BGHORSECK,Main            ,7675.7
2176.694
River Rch & RM=BGHORSECK,Main            ,1686.8
3371.998
Boundary for River Rch & Prof#=BGHORSECK,Main            , 1
Up Type= 0
Dn Type= 3
Dn Slope=0.00321
DSS Import GetInterval= 0
DSS Import GetPeak= 0
DSS Import FillOption= 0

--- BGHORSECK.g01 (geometry) ---

Geom Title=USGS 10m DEM
Program Version=4.10

River Reach=BGHORSECK       ,Main
Reach XY= 30
     1708361.082      401957.642      1708558.43      402271.582
     1709325.173      402602.361     1709491.854      402867.877
     1709876.759      403052.152      1710478.65      403752.879
     1710689.126      403863.282      1710803.78      404420.032
     1710567.317      405319.991     1710875.176      405938.776
     1712191.759      406569.223     1712112.766      408087.365
      1711642.28      408599.518     1711505.301      408932.157
     1710780.128      409227.209     1710706.343      409531.462
     1711388.287      410403.598     1711282.384       410926.08
     1711581.777      411564.883     1711457.645      412070.004
     1711867.367      413176.341     1712323.009       413640.49
     1712283.079      413789.796     1711928.044      413938.233
     1711242.975      414981.636      1710990.37      415170.872
      1711046.61      416217.164     1711761.367      416644.595
     1711748.346      416830.359      1711527.86      416980.532

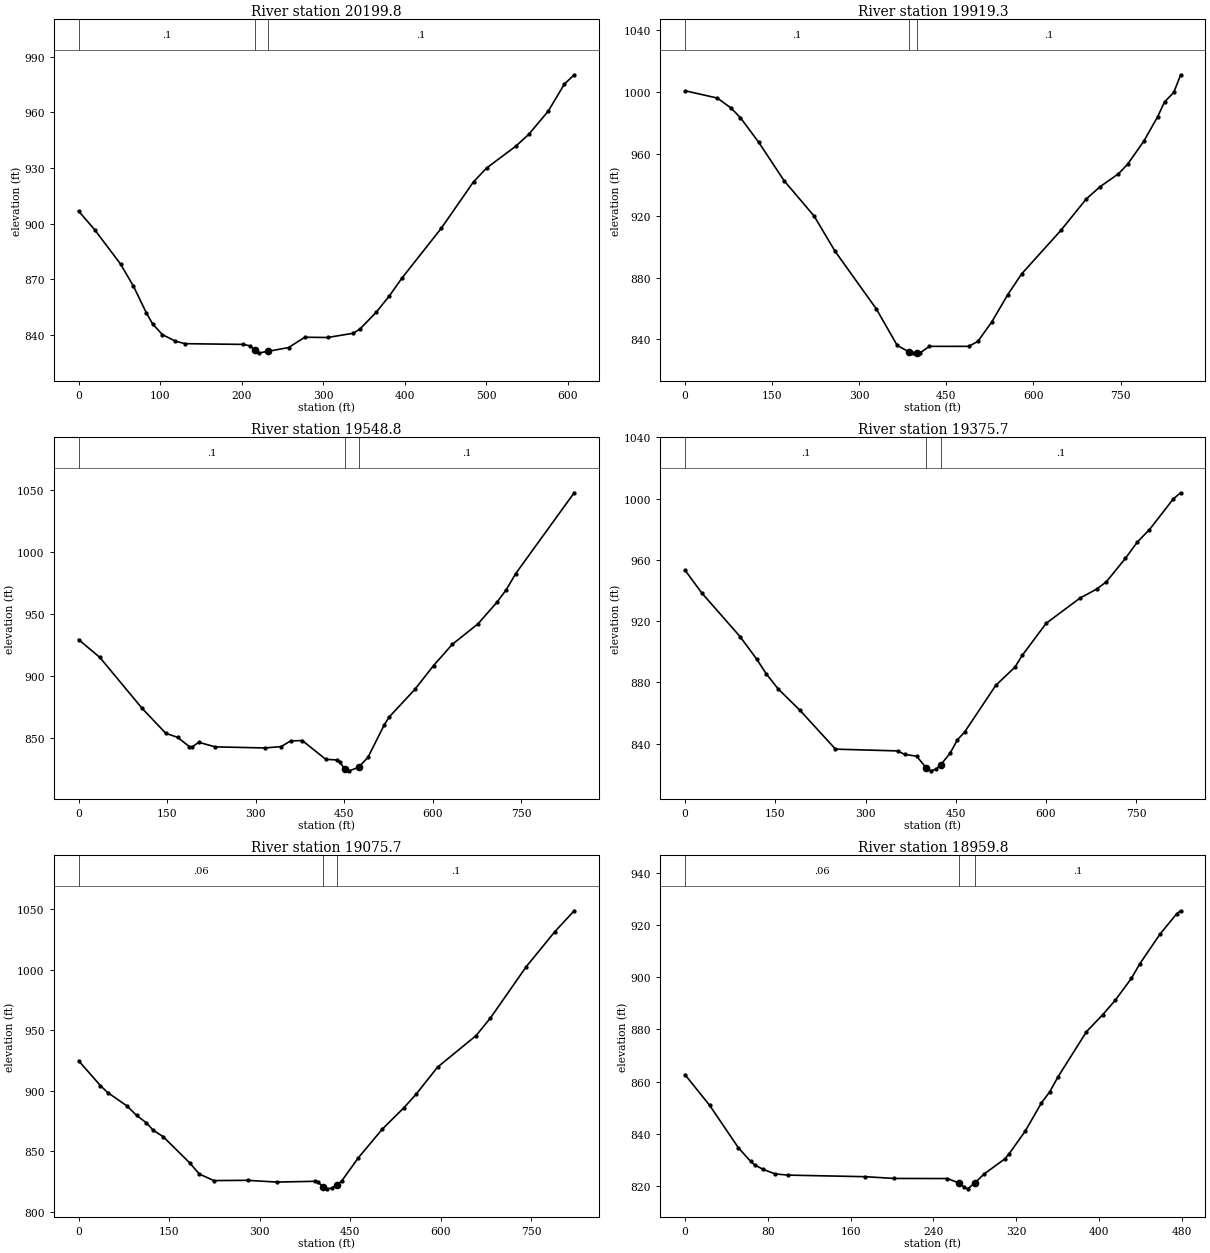
Type RM Length L Ch R = 1 ,20199.8 ,291,280.5,270.9
XS GIS Cut Line= 3
     1708195.026      402143.192     1708361.692      402052.046
      1708733.79      401861.372
#Sta/Elev= 30
       0  906.79    19.8  896.68    51.4  878.27    67.3  866.31    83.1  851.95
      91  845.84   102.9  840.22   118.7  836.71   130.6  835.35   201.9  834.95
   209.9  834.22     217  831.71   221.8  830.41     232  831.19   257.6  833.25
   277.6  838.81   305.4  838.68   337.3  840.98   345.3  843.29   365.2  852.29
   381.1  860.98     397  870.83   444.8  897.42   484.6  922.57   500.6  929.99
   536.4  941.74   552.3  948.12   576.2  960.62   596.1  975.23   608.1  980.25
#Mann= 3 , 0 , 0
       0      .1       0     217    .045       0     232      .1       0
Bank Sta=217,232
XS Rating Curve= 0 ,0
Exp/Cntr=0.3,0.1

Type RM Length L Ch R = 1 ,19919.3 ,370.5,370.5,367.1
XS GIS Cut Line= 3
     1708299.028      402549.049     1708556.897      402226.659
      1708845.01      401893.286
#Sta/Elev= 30
       0 1000.91    55.6  996.19    79.4  989.64    95.3  983.48     127  967.46
   170.7  942.62   222.3  919.81     258  897.21   329.5  859.66   365.2   836.2
     385  832.07     393  831.34     400  831.49   404.9  831.37   420.8  835.54
   488.3  835.53   504.1  838.71     528  851.23   555.7  869.01   579.6  882.43
     647  910.51   690.7  930.85   714.5  938.79   746.3  947.18   762.2  953.43
   789.9  968.24   813.8  984.12   825.7  993.71   841.6  999.87   853.4 1011.26
#Mann= 3 , 0 , 0
       0      .1       0     385    .045       0     400      .1       0
Bank Sta=385,400
XS Rating Curve= 0 ,0
Exp/Cntr=0.3,0.1

Type RM Length L Ch R = 1 ,19548.8 ,175.6,173.1,172.3
XS GIS Cut Line= 3
     1708450.668      402486.942     1708799.626      402446.577
     1709048.324      402026.004
#Sta/Elev= 30
       0  929.25    35.9  914.93   107.8  873.85   147.7  853.87   167.7  850.62
   187.6  843.22   191.6  842.65   203.6  846.63   231.5  842.96   315.4  842.09
   343.3  843.18   359.2  847.74   379.1  848.03   418.8  832.96   438.7  832.38
   442.6  830.95     451  824.82   458.5  823.67   474.4  826.47   490.3  834.48
   518.1  860.72   526.1  866.86   569.8  889.16   601.5  908.33   633.3  925.41
     677  941.98   708.8   959.2   724.7  969.31   740.6  982.21   839.9 1047.38
#Mann= 3 , 0 , 0
       0      .1       0     451    .045       0   474.4      .1       0
Bank Sta=451,474.4
XS Rating Curve= 0 ,0
Exp/Cntr=0.3,0.1

Type RM Length L Ch R = 1 ,19375.7 ,294.2,300,302.7
XS GIS Cut Line= 3
     1708836.493      402809.377     1709002.594      402435.979
     1709199.873      402070.825
#Sta/Elev= 30
       0  953.13    27.8  938.31    91.3   909.9     119  895.16   134.9  885.55
   154.7  875.69   190.4  861.97     250  836.39   353.1  835.24     365  832.96
   384.9  831.78   401.2  823.98   408.7  822.23   416.7  823.32   424.6  826.02
   440.6  833.78   452.6  842.48   464.6  847.53   516.4  878.01   548.4  889.98
   560.3  897.54   600.2  918.54   656.1  934.91     684  940.84     700  945.54
   731.9  960.94   751.9  971.67   771.8  979.65   811.7  999.84   823.7 1003.74
#Mann= 3 , 0 , 0
       0      .1       0   401.2    .045       0   424.6      .1       0
Bank Sta=401.2,424.6
XS Rating Curve= 0 ,0
Exp/Cntr=0.3,0.1

Type RM Length L Ch R = 1 ,19075.7 ,111.7,115.9,118.3
XS GIS Cut Line= 3
     1709020.977      402890.744     1709268.003      402561.252
     1709523.559      402241.803
#Sta/Elev= 30
       0  924.65      36  904.19      48  898.44      80  887.36      96   879.5
     112  873.49   123.9  867.11   139.9  862.04   183.9  840.37   199.9   831.1
   223.9  825.68   279.9  825.89   327.8  824.45   391.8  825.09   395.8  824.85
   404.3  820.69   411.8  818.86   419.8  819.51   427.7  822.29   435.6  825.21
   463.4  844.56   503.2  868.26   538.9  885.88   558.8  896.85   594.5  919.35
   658.1   945.3   681.9  959.78   741.5 1002.39   789.1  1031.4   820.9 1048.55
#Mann= 3 , 0 , 0
       0     .06       0   404.3    .045       0   427.7      .1       0
Bank Sta=404.3,427.7
XS Rating Curve= 0 ,0
Exp/Cntr=0.3,0.1

Type RM Length L Ch R = 1 ,18959.8 ,192.7,232.9,410.1
XS GIS Cut Line= 3
     1709156.831      402818.105     1709352.144      402638.418
     1709504.487      402488.678
#Sta/Elev= 30
       0  862.61    23.8  850.86    51.5  834.65    63.4  829.42    67.3  828.07
    75.3  826.39    87.1  824.64      99  824.18   174.3  823.57     202   822.9
   253.5  822.86   265.1  821.12   269.4  819.66   273.3  818.92   280.1  821.23
   289.1  824.62   308.9  830.34   312.9  832.18   328.7  840.98   344.5  851.86
   352.4  856.04   360.3   861.7     388  879.12   403.8  885.67   415.7   891.1
   431.5  899.58   439.4  905.04   459.2  916.54     475  924.18     479  925.41
#Mann= 3 , 0 , 0
       0     .06       0   265.1    .045       0   280.1      .1       0
Bank Sta=265.1,280.1
XS Rating Curve= 0 ,0
Exp/Cntr=0.3,0.1

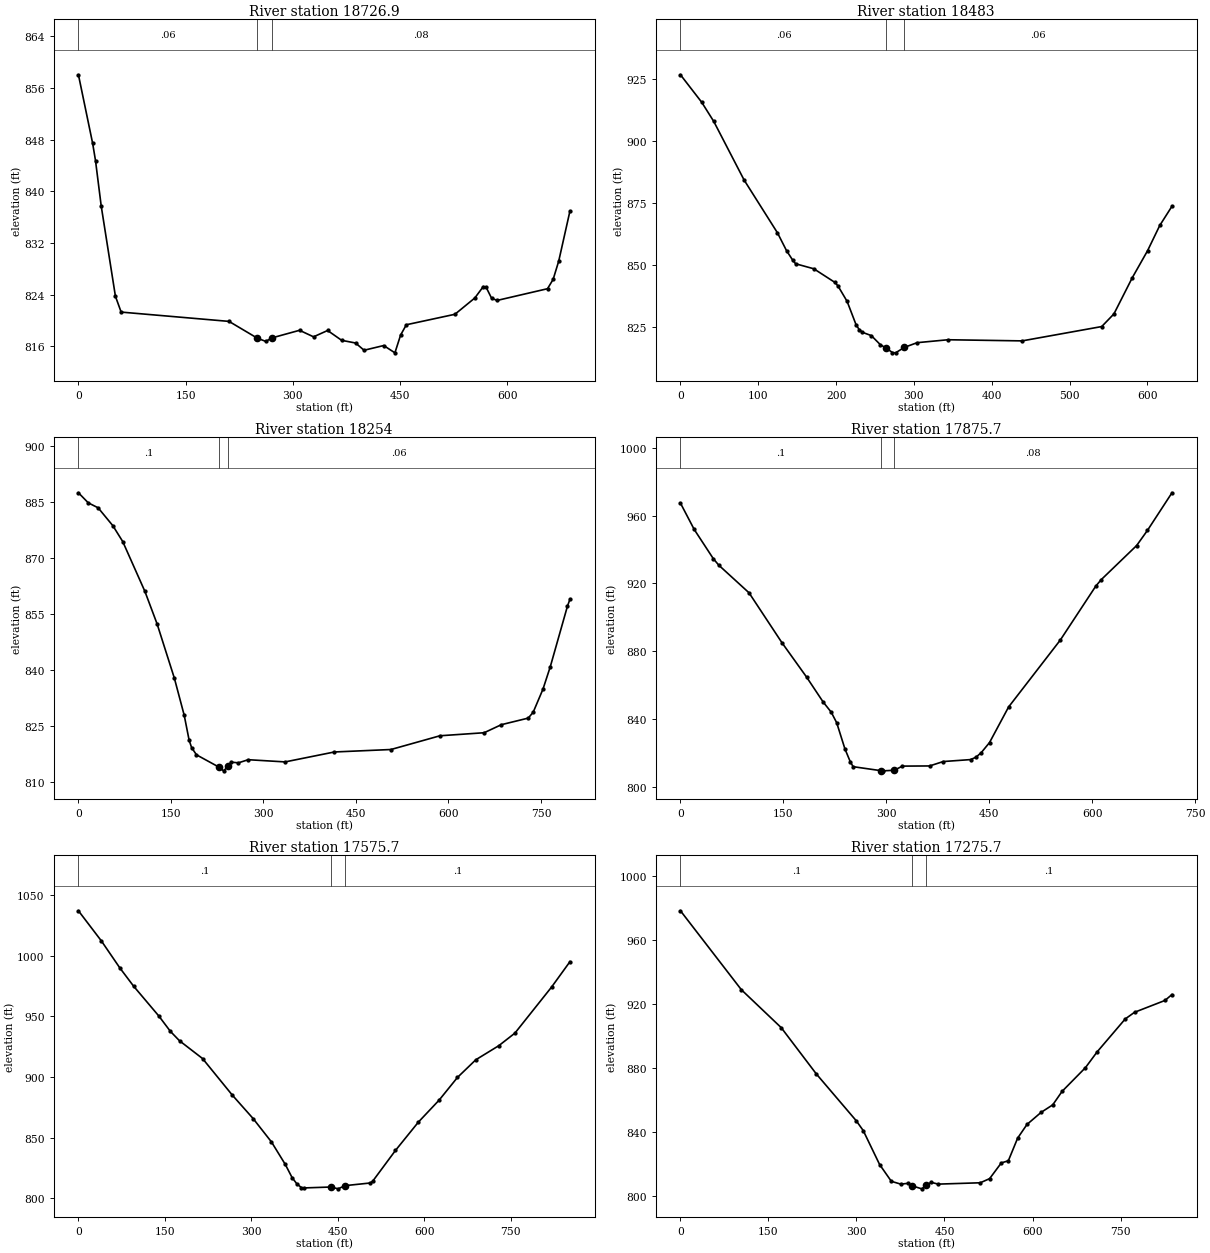
Type RM Length L Ch R = 1 ,18726.9 ,289.2,243.9,60.7
XS GIS Cut Line= 6
     1709261.866      402845.015     1709363.428      402755.171
     1709474.105      402838.504     1709616.727      402928.956
     1709673.375       402832.45     1709717.595      402706.994
#Sta/Elev= 30
       0  858.03    19.9  847.41    23.9  844.74    31.9   837.7    51.8  823.72
    59.8  821.28   210.8  819.84   250.4  817.24   262.3  816.74   270.7  817.28
   309.5  818.46   329.1  817.45   348.8  818.43   368.4  816.91     388  816.49
   399.8  815.37   427.3   816.1     443  814.97     451  817.73     459  819.32
     527  820.94   554.9  823.47   566.7  825.23   570.6  825.14   578.4  823.41
   586.2  823.09   656.6   824.9   664.5  826.35   672.3  829.18     688  836.93
#Mann= 3 , 0 , 0
       0     .06       0   250.4    .045       0   270.7     .08       0
Bank Sta=250.4,270.7
XS Rating Curve= 0 ,0
Exp/Cntr=0.3,0.1

Type RM Length L Ch R = 1 ,18483   ,224.1,229,233.3
XS GIS Cut Line= 5
       1709449.8      403086.334     1709597.334      403074.128
       1709662.5      402968.103      1709770.98      402802.046
     1709779.661      402641.456
#Sta/Elev= 30
       0  926.56    27.3  915.48    42.8  907.74    81.8  884.11   124.7   862.8
   136.4  855.58   144.1  851.88     148  850.34   171.4  848.32   198.6   842.8
   202.5  841.37   214.2  835.16   225.8  825.66   229.7  823.82   233.6  822.73
   245.3  821.37   256.9   817.7   264.7  816.26   272.5  814.52   276.5  814.42
   287.7  816.62   304.2  818.52   343.9   819.7   439.1  819.24   541.4  825.02
   557.1  830.12   580.7  844.73   600.3  855.59     616  865.79   631.7  873.54
#Mann= 3 , 0 , 0
       0     .06       0   264.7    .045       0   287.7     .06       0
Bank Sta=264.7,287.7
XS Rating Curve= 0 ,0
Exp/Cntr=0.3,0.1

Type RM Length L Ch R = 1 ,18254   ,373.6,378.3,380.7
XS GIS Cut Line= 4
     1709711.953      403220.449     1709836.374      403091.115
     1710059.175      402862.376     1709935.477      402591.109
#Sta/Elev= 30
       0   887.4      16   884.7    31.9  883.38    55.8  878.59    71.8  874.35
   107.7  861.03   127.6  852.27   155.5  837.79   171.5  827.84   179.5  821.14
   183.5  819.18   191.4  817.25   227.9  813.95   235.4  812.96   242.9  814.27
   247.3   815.3   259.3   815.1   275.3  815.94   335.1  815.35     415  818.01
   506.7  818.67   586.2  822.35   657.8  823.16   685.6  825.31   729.3  827.08
   737.3  828.65   753.2  834.84   765.1  840.87   792.9  857.07   796.9  858.89
#Mann= 3 , 0 , 0
       0      .1       0   227.9    .045       0   242.9     .06       0
Bank Sta=227.9,242.9
XS Rating Curve= 0 ,0
Exp/Cntr=0.3,0.1

Type RM Length L Ch R = 1 ,17875.7 ,297.9,300,299.6
XS GIS Cut Line= 3
     1709892.074      403500.397     1710128.984      403316.935
     1710449.145      403050.226
#Sta/Elev= 30
       0   967.3      20  951.79    47.9   934.5    55.9  930.65    99.9  914.38
   147.8  884.97   183.8  864.62   207.8  849.99   219.7  843.91   227.7  837.63
   239.7   822.2   247.7  814.42   251.7  811.72   292.1  809.37   295.6  809.27
   311.6  809.61   323.4  812.06   363.1  812.16     383  814.76   422.7  815.91
   430.6  817.29   438.5  820.09   450.4  825.96   478.2  846.97   553.6   886.5
   605.2  918.28   613.2  922.14   664.8  942.27   680.6  951.24   716.3  973.42
#Mann= 3 , 0 , 0
       0      .1       0   292.1    .045       0   311.6     .08       0
Bank Sta=292.1,311.6
XS Rating Curve= 0 ,0
Exp/Cntr=0.3,0.1

Type RM Length L Ch R = 1 ,17575.7 ,300.3,300,297.3
XS GIS Cut Line= 3
     1709968.949      403752.563     1710343.982      403503.019
     1710655.504       403248.51
#Sta/Elev= 30
       0 1037.32    39.9 1012.37    71.8  990.15    95.7  975.06   139.5  950.39
   159.5  937.74   175.4  929.93   215.3  915.28   267.1  884.98     303  865.73
   334.9  846.37   358.8  827.86   370.7  816.91   378.7  811.91   386.7  808.68
   390.7  808.38   438.5  809.15   450.5  807.64   462.4  810.27   506.2  812.47
   510.2  813.75     550  839.35   589.9  862.84   625.7  880.89   657.6  899.68
   689.4  914.25   729.3  925.89   757.2  936.25   820.9  974.35   852.7  995.27
#Mann= 3 , 0 , 0
       0      .1       0   438.5    .045       0   462.4      .1       0
Bank Sta=438.5,462.4
XS Rating Curve= 0 ,0
Exp/Cntr=0.3,0.1

Type RM Length L Ch R = 1 ,17275.7 ,308.1,317.7,328.6
XS GIS Cut Line= 3
     1710161.909      404006.543     1710461.487       403730.53
     1710777.398      403438.326
#Sta/Elev= 30
       0  978.09   103.8  928.81   171.7  905.16   231.6  876.24   299.5  847.08
   311.5  840.91   339.4  819.73   359.4  809.24   375.4   807.5   387.4  807.96
   395.4  806.37   411.3  804.55   419.3  806.81   427.3  808.61   439.2   807.5
   510.9  808.33   526.9  810.91   546.8  820.72   558.8  822.07   574.7  836.23
   590.6  844.74   614.5  852.23   634.5  856.98   650.4  865.37   690.2  880.17
   710.2  890.06     758  910.57   773.9  914.74   825.7  922.12   837.7  925.82
#Mann= 3 , 0 , 0
       0      .1       0   395.4    .045       0   419.3      .1       0
Bank Sta=395.4,419.3
XS Rating Curve= 0 ,0
Exp/Cntr=0.3,0.1

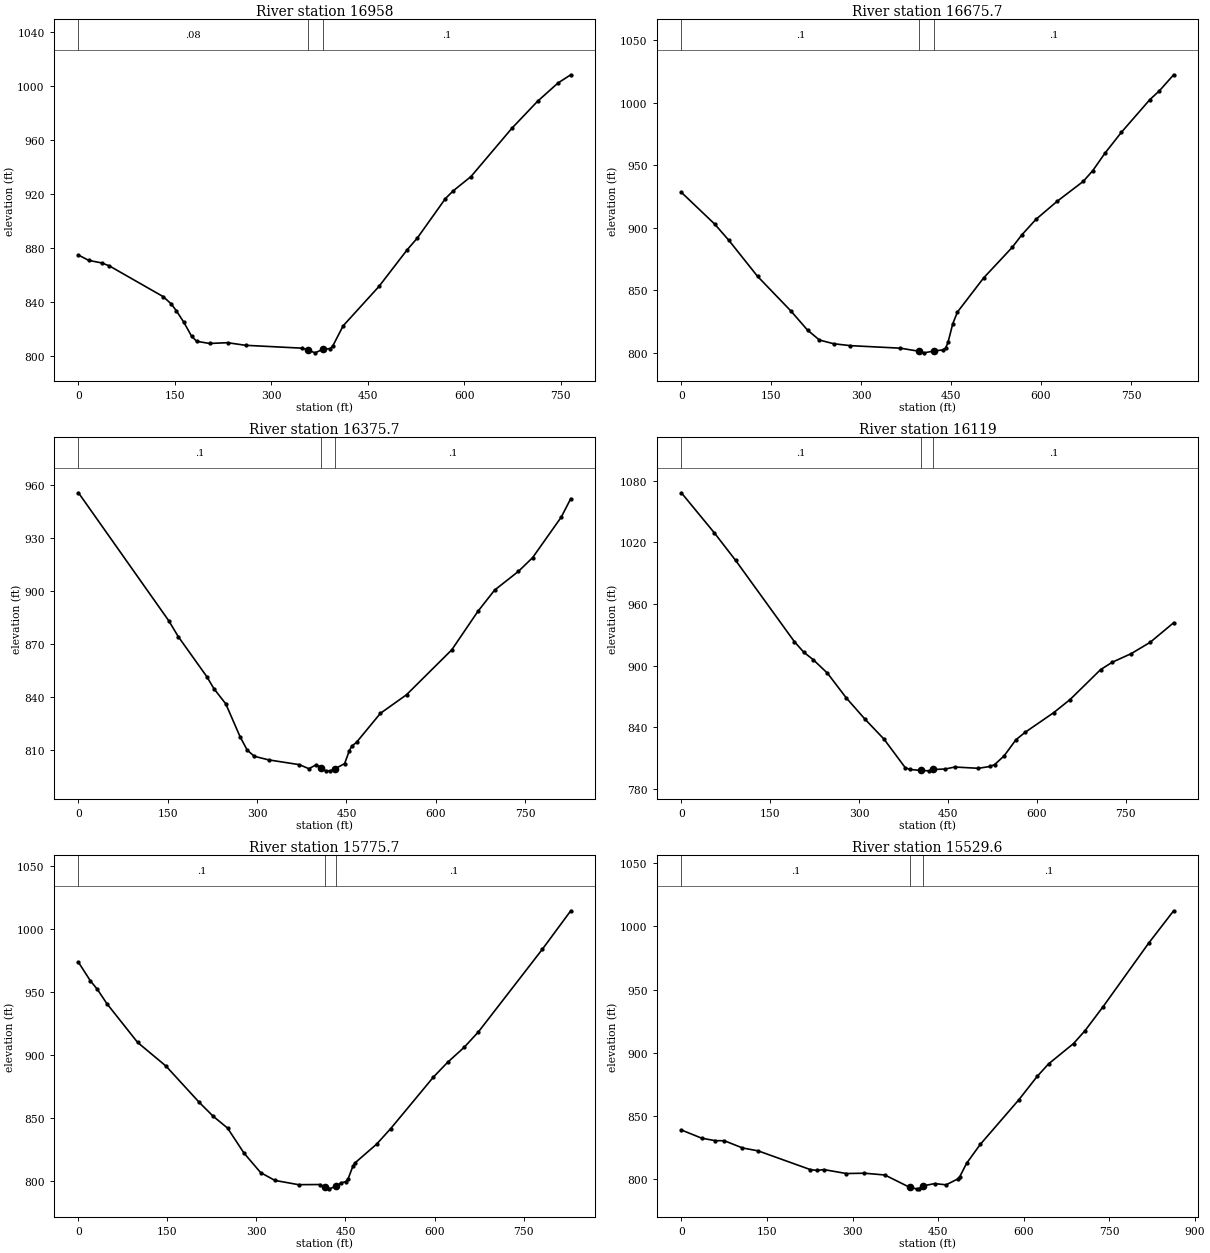
Type RM Length L Ch R = 1 ,16958   ,278.4,282.3,285.1
XS GIS Cut Line= 3
     1710358.654       404025.57     1710705.876      403904.043
     1711091.011      403804.753
#Sta/Elev= 30
       0  874.89      16  870.96      36  869.08      48  866.89     132  844.05
     144  838.81     152   833.8   163.9  825.08   175.9  814.81   183.9  811.01
   203.9  809.42   231.9  809.98   259.9  808.05   347.9  805.92   356.2  804.68
   367.9  802.47   379.8  805.03   391.7  805.66   395.7  807.74   411.6  822.46
   467.3  851.64   511.1  878.74     527  887.52   570.7  916.76   582.6   922.4
   610.5  933.09   674.1  968.86   713.9  988.78   745.7 1002.34   765.6 1008.45
#Mann= 3 , 0 , 0
       0     .08       0   356.2    .045       0   379.8      .1       0
Bank Sta=356.2,379.8
XS Rating Curve= 0 ,0
Exp/Cntr=0.3,0.1

Type RM Length L Ch R = 1 ,16675.7 ,291.7,300,307.4
XS GIS Cut Line= 3
     1710363.792      404251.161     1710766.137      404176.915
     1711174.006       404118.66
#Sta/Elev= 30
       0  928.39    55.6  903.03    79.4  889.97   127.1  861.31   182.7  833.66
   210.5  818.37   230.4  810.44   254.2  807.47     282  805.96   365.4  803.94
   397.2  801.42   405.2  800.22     421   801.7   436.9  802.58   440.8  804.01
   444.8  808.49   452.7  823.39   460.6  832.82   504.2  860.02   551.8  884.39
   567.6  894.21   591.4  906.76     627  921.28   670.6  937.19   686.4  945.78
   706.3  959.42     734   976.3   781.5  1002.4   797.4 1009.43   821.2 1022.25
#Mann= 3 , 0 , 0
       0      .1       0   397.2    .045       0     421      .1       0
Bank Sta=397.2,421
XS Rating Curve= 0 ,0
Exp/Cntr=0.3,0.1

Type RM Length L Ch R = 1 ,16375.7 ,256.2,256.8,256.5
XS GIS Cut Line= 3
     1710379.737      404400.056     1710788.655      404470.598
     1711192.313      404551.044
#Sta/Elev= 30
       0  955.65   151.6   883.2   167.6   874.2   215.5  851.54   227.4  844.76
   247.4  836.11   271.3  817.56   283.3  809.96   295.3  806.45   319.2  804.42
   371.1   801.7     387   799.4     399  801.66   407.5  800.09     415  798.23
     423  798.21   430.9   799.4   446.9  802.31   454.9  809.71   458.9  812.16
   466.9  814.37   506.9  830.75   550.8  841.29   626.8  866.72   670.7  888.52
   698.7  900.53   738.6  911.11   762.6  918.94   810.6  941.85   826.6  952.34
#Mann= 3 , 0 , 0
       0      .1       0   407.5    .045       0   430.9      .1       0
Bank Sta=407.5,430.9
XS Rating Curve= 0 ,0
Exp/Cntr=0.3,0.1

Type RM Length L Ch R = 1 ,16119   ,340.1,343.2,346.8
XS GIS Cut Line= 3
     1710317.036      404633.345     1710723.237      404711.334
      1711132.37      404792.957
#Sta/Elev= 30
       0 1068.37    55.7  1029.3    91.5 1002.55   190.9   923.2   206.8  912.92
   222.7  905.66   246.6  892.56   278.4  868.44   310.2  847.59     342  828.32
   377.8  800.54   385.8  798.78   404.1  797.83   417.6  797.43   425.5  798.77
   445.4  799.19   461.3  801.16     501  799.91   520.9  801.67   528.8  803.56
   544.7     812   564.6  827.69   580.5  835.11   628.2  854.05     656  866.88
   707.6   896.1   727.5  903.33   759.3  911.67   791.1  922.64   830.8  941.72
#Mann= 3 , 0 , 0
       0      .1       0   404.1    .045       0   425.5      .1       0
Bank Sta=404.1,425.5
XS Rating Curve= 0 ,0
Exp/Cntr=0.3,0.1

Type RM Length L Ch R = 1 ,15775.7 ,251.2,246.1,239.8
XS GIS Cut Line= 3
     1710293.736      404913.559     1710695.939      405043.193
     1711076.701      405187.018
#Sta/Elev= 30
       0  973.47    19.9   958.9    31.9  951.98    47.8  940.73    99.7   909.9
   147.5  891.14   203.3  862.47   227.2  851.26   251.2  841.98   279.1  822.01
     307  806.64   330.9  800.46   370.8  797.07   406.6  797.18   415.1  795.13
   422.6  793.76   434.6  795.92   442.5   798.5   450.5  799.48   454.5  801.81
   462.5  811.76   466.5  814.53   502.4   829.2   526.3  841.61   598.2  882.44
   622.1  894.14     650  906.03     674  918.28   781.7   983.8   829.6 1014.34
#Mann= 3 , 0 , 0
       0      .1       0   415.1    .045       0   434.6      .1       0
Bank Sta=415.1,434.6
XS Rating Curve= 0 ,0
Exp/Cntr=0.3,0.1

Type RM Length L Ch R = 1 ,15529.6 ,366,353.9,341.4
XS GIS Cut Line= 3
     1710179.106      405227.836     1710577.838      405260.379
     1711038.416      405301.281
#Sta/Elev= 30
       0  838.81    35.6  832.32    59.4  830.34    75.3   830.3     107  824.59
   134.7  822.24   225.8  807.45   237.7  806.74   249.5  807.44   289.2  804.31
   320.8  804.57   356.5  803.15   400.1  793.36     412  792.19     416  792.31
     424  794.61   443.9  796.33   463.8  795.37   483.8  799.92   487.8  801.82
   499.7  812.44   523.6  827.36   591.4  862.84   623.3  881.22   643.2  891.12
   687.1  907.29     707  917.38   738.9  936.52   818.6  986.76   862.4 1012.42
#Mann= 3 , 0 , 0
       0      .1       0   400.1    .045       0     424      .1       0
Bank Sta=400.1,424
XS Rating Curve= 0 ,0
Exp/Cntr=0.3,0.1

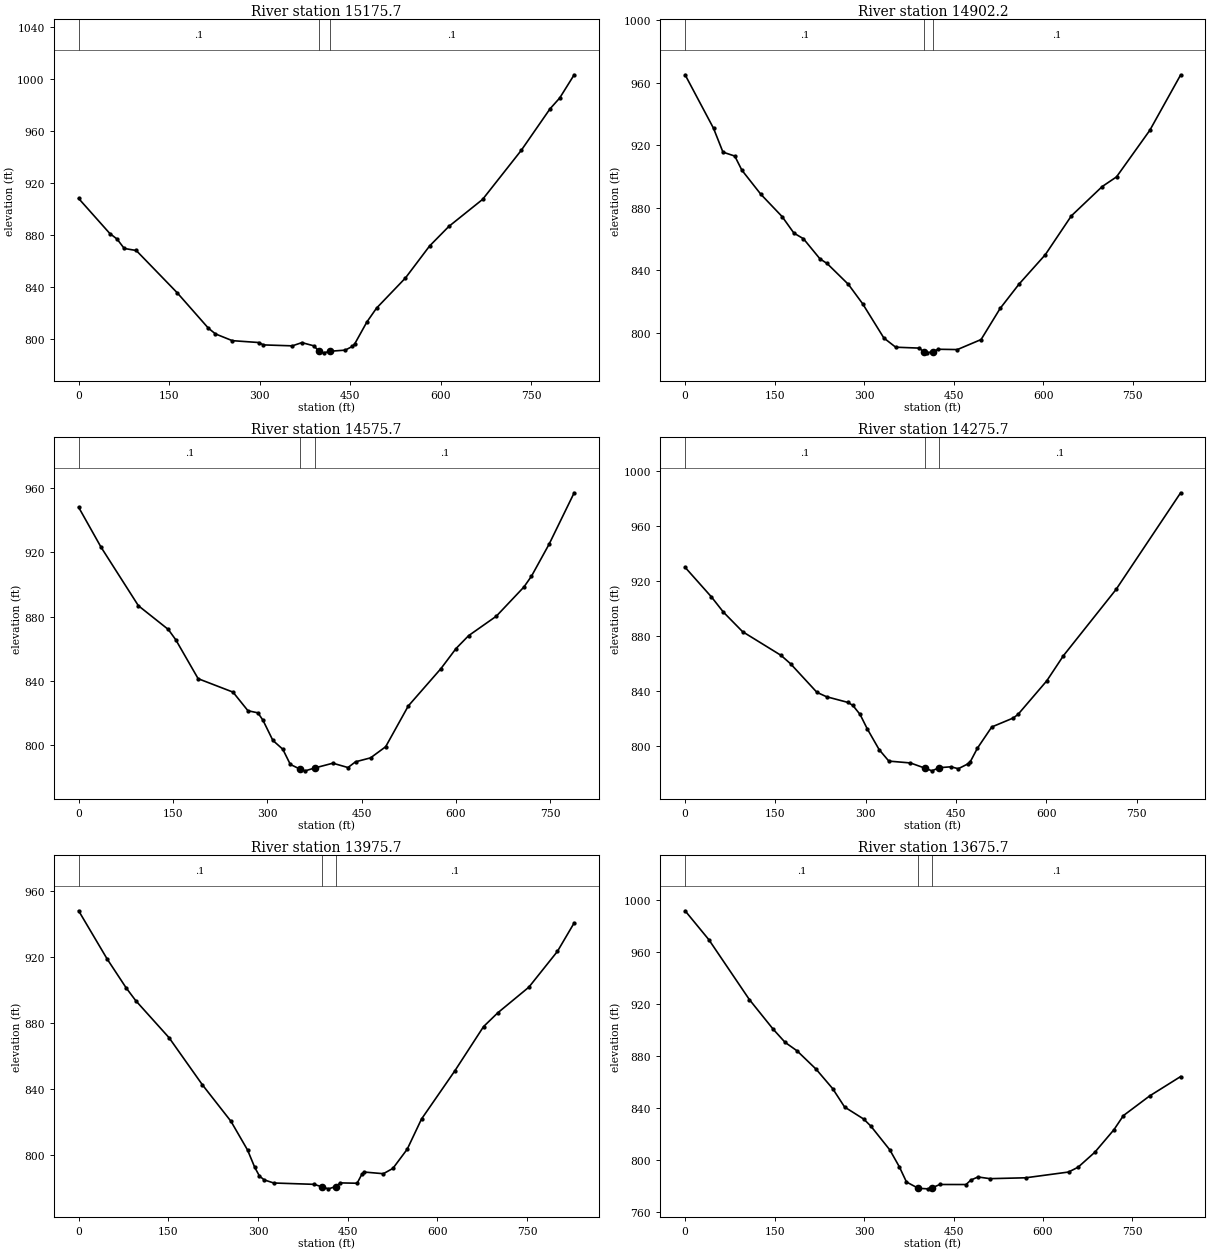
Type RM Length L Ch R = 1 ,15175.7 ,271.6,273.5,272.5
XS GIS Cut Line= 3
     1710339.641      405760.547     1710702.994      405570.853
     1711071.569      405387.899
#Sta/Elev= 30
       0  907.95    51.7  880.97    63.7   876.7    75.6  869.46    95.5  867.89
   163.2  835.44   214.9  808.17   226.8  803.67   254.7  798.48   298.5  797.04
   306.4  795.21   354.2  794.48   370.1  796.98     390  794.47     398  790.49
   405.9   789.1   417.4  790.35   441.8  791.18   453.8  794.06   457.8  796.13
   477.8  812.86   493.8  823.52   541.7  846.72   581.7  871.34   613.6   886.4
   669.6  907.23   733.5  944.88   781.4  976.98   797.4  985.29   821.4 1003.17
#Mann= 3 , 0 , 0
       0      .1       0     398    .045       0   417.4      .1       0
Bank Sta=398,417.4
XS Rating Curve= 0 ,0
Exp/Cntr=0.3,0.1

Type RM Length L Ch R = 1 ,14902.2 ,341.4,326.5,314
XS GIS Cut Line= 3
     1710445.538      405977.053     1710823.064      405811.595
     1711188.732        405609.6
#Sta/Elev= 30
       0  965.01    47.6  930.81    63.4  915.57    83.2  913.05    95.1  904.03
   126.8  888.65   162.5  874.36   182.3  863.79   198.2  860.22   225.9  847.34
   237.8  844.39   273.5  831.03   297.2  818.73   332.9  796.76   352.7  790.88
   392.4   790.3   399.9  787.72   404.3  787.28   414.9  788.06   424.1  789.57
     456  789.37   495.7  795.78   527.6  815.66   559.4  831.28   603.2  849.99
   646.9  874.84   698.6  893.59   722.5  899.74   778.2  929.48   829.9  964.92
#Mann= 3 , 0 , 0
       0      .1       0   399.9    .045       0   414.9      .1       0
Bank Sta=399.9,414.9
XS Rating Curve= 0 ,0
Exp/Cntr=0.3,0.1

Type RM Length L Ch R = 1 ,14575.7 ,296.2,300,299.3
XS GIS Cut Line= 3
     1710862.126      406354.129     1711034.203       406037.64
     1711249.646      405668.295
#Sta/Elev= 30
       0  948.09    35.6  923.29      95  886.87   142.5  872.13   154.4  865.72
     190   841.5   245.4  833.15   269.2  821.57     285  820.26     293   815.7
   308.8  803.12   324.6  797.63   336.5  788.21   352.7  785.12   360.2   784.2
   376.2  786.07   404.2  788.95   428.2  786.25   440.2  789.82   464.1  792.27
   488.1  799.19   524.1  824.56     576  847.78     600  860.26     620  868.26
     664  880.35   707.9  898.51   719.9  905.23   747.9  925.11   787.8   957.1
#Mann= 3 , 0 , 0
       0      .1       0   352.7    .045       0   376.2      .1       0
Bank Sta=352.7,376.2
XS Rating Curve= 0 ,0
Exp/Cntr=0.3,0.1

Type RM Length L Ch R = 1 ,14275.7 ,304.5,300,296.7
XS GIS Cut Line= 3
     1711061.127      406481.939     1711306.698      406153.756
     1711514.985      405797.187
#Sta/Elev= 30
       0  929.98    43.8  908.36    63.7  897.26    95.5  883.05   159.2  865.82
   175.1  859.68   218.9  838.84   234.8  835.66   270.6  831.47   278.6  829.28
   290.5  822.75   302.4  812.29   322.3  797.03   338.3  788.73   374.1  787.38
     398  783.63   409.9  781.63   421.8  783.94   441.6  784.57   453.6  783.17
   469.4  786.66   473.4  788.14   485.3   798.1   509.2  813.61   544.9  820.14
   552.8  822.76   600.5  847.22   628.3  865.63   715.6  913.85   822.8   984.3
#Mann= 3 , 0 , 0
       0      .1       0     398    .045       0   421.8      .1       0
Bank Sta=398,421.8
XS Rating Curve= 0 ,0
Exp/Cntr=0.3,0.1

Type RM Length L Ch R = 1 ,13975.7 ,295.9,300,303.5
XS GIS Cut Line= 3
     1711394.954      406623.772     1711581.361      406254.114
     1711746.692      405873.489
#Sta/Elev= 30
       0  948.04    47.8  918.78    79.6  901.29    95.5  893.61   151.3  871.14
     207  842.63   254.8  820.52   282.6   803.1   294.6  792.62   302.5  787.34
   310.5  785.01   326.4  783.13   394.1  782.31   406.5  780.85     418  779.59
     430  780.95   437.9  783.19   465.9  782.98   473.8  788.41   477.8  789.76
   509.8  788.76   525.7  791.96   549.7   803.6   573.6  821.88   629.5  851.15
   677.4  877.88   701.3  886.26   753.2  901.76     801  923.45     829   940.7
#Mann= 3 , 0 , 0
       0      .1       0   406.5    .045       0     430      .1       0
Bank Sta=406.5,430
XS Rating Curve= 0 ,0
Exp/Cntr=0.3,0.1

Type RM Length L Ch R = 1 ,13675.7 ,139.3,142.3,145.3
XS GIS Cut Line= 3
      1711591.21      406717.866     1711828.297      406387.011
     1712059.194      406031.807
#Sta/Elev= 30
       0  991.37    39.9  969.11   107.7  923.18   147.6  900.42   167.6   890.3
   187.6   883.8   219.5  869.73   247.4  854.73   267.4   840.6   299.3  831.39
   311.3  825.99   343.2  807.66   359.2  794.63   371.1     783   391.1  778.14
     407  777.75   414.5  778.62     427  781.09     471  781.06     479  784.47
     491  786.87     511  785.57   570.9  786.24   642.8  790.66   658.8  794.38
   686.8  805.84   718.8  823.12   734.8  834.04   778.7  849.11   830.7  864.02
#Mann= 3 , 0 , 0
       0      .1       0   391.1    .045       0   414.5      .1       0
Bank Sta=391.1,414.5
XS Rating Curve= 0 ,0
Exp/Cntr=0.3,0.1

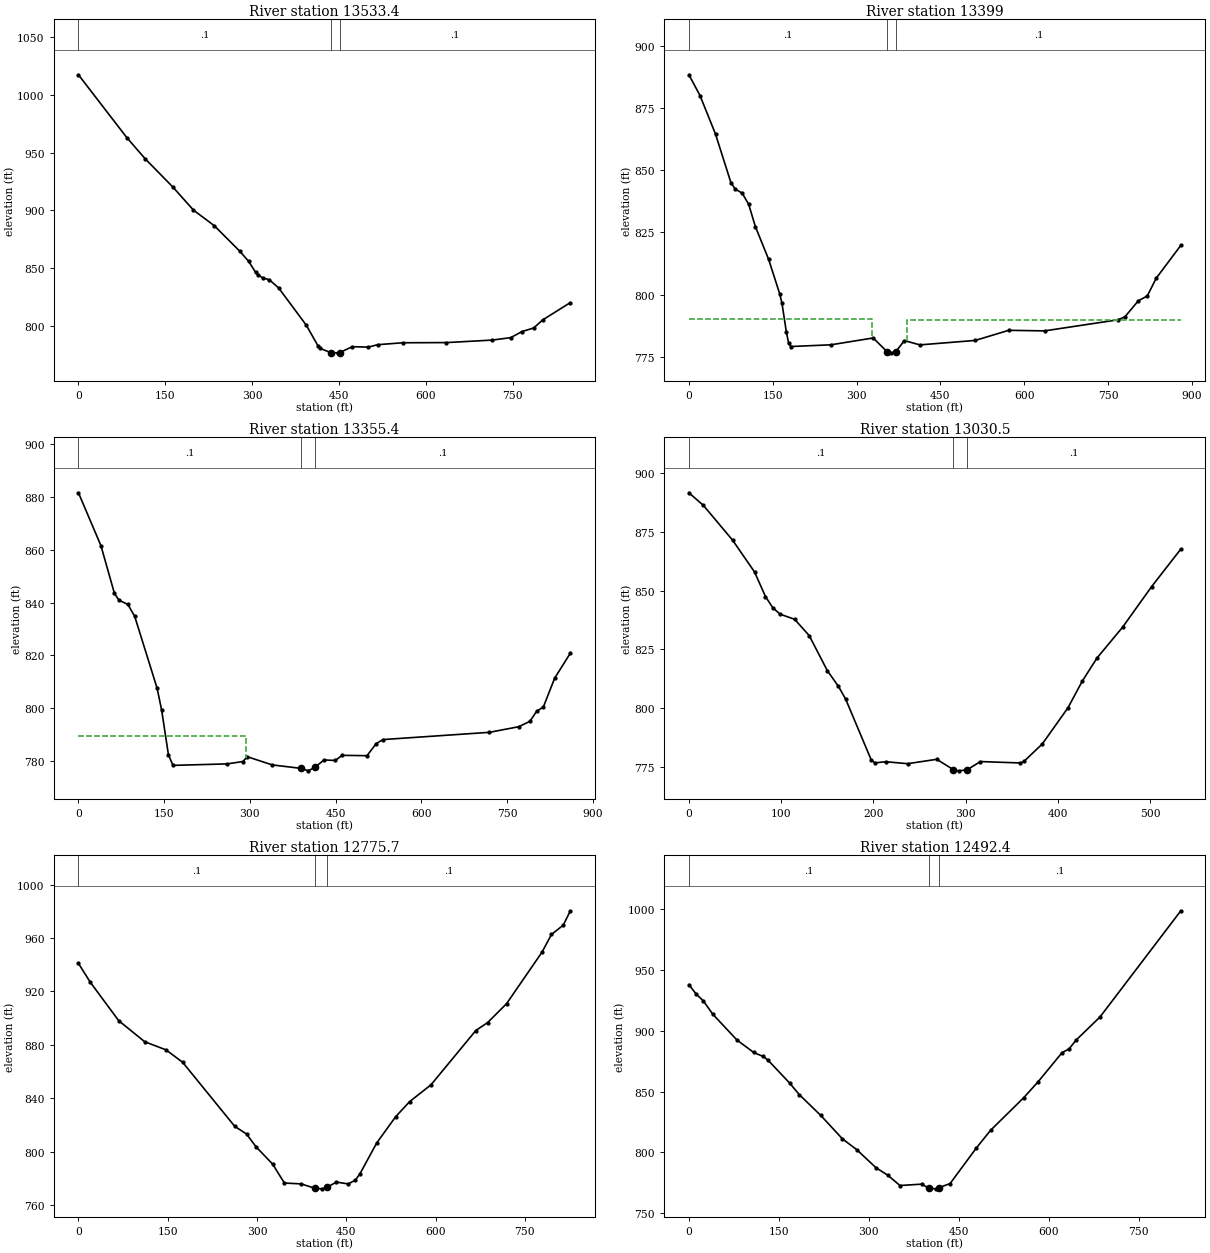
Type RM Length L Ch R = 1 ,13533.4 ,152.9,134.4,33.3
XS GIS Cut Line= 3
     1711666.637      406769.543     1712002.751      406387.984
      1712188.72       406102.46
#Sta/Elev= 30
       0 1017.18    83.4  962.94   115.2  944.57   162.9  920.23   198.6  900.21
   234.4   886.8   278.1  864.93     294  855.86   305.9  846.38   309.9  844.28
   317.8  841.79   329.7  839.99   345.6  832.97   393.3  800.82   413.2  783.23
   417.1  780.76     436  776.98   448.9  776.89     451  777.15   472.7   782.2
   500.5  781.83   516.4  783.93     560   785.6   635.3  785.75   714.5  787.92
   746.2  790.02     766  795.33   785.8  798.37   801.7  805.42   849.2   820.3
#Mann= 3 , 0 , 0
       0      .1       0     436    .045       0     451      .1       0
Bank Sta=436,451
XS Rating Curve= 0 ,0
Exp/Cntr=0.3,0.1

Type RM Length L Ch R = 1 ,13399   ,41.8,43.6,128.5
XS GIS Cut Line= 5
     1711904.053      406723.747     1712081.137      406680.345
     1712077.664       406477.22     1711992.595      406426.872
     1712216.553      406100.484
#Sta/Elev= 30
       0  888.38    19.8  880.04    47.6  864.51    75.3   844.9    83.2  842.34
    95.1  840.84     107  836.25   118.9  827.32   142.7  814.11   162.5  800.23
   166.5  796.52   174.4  784.84   178.4  780.47   182.3  779.08     254  779.77
   329.7  782.52   355.2  776.87   361.6  776.54   370.2  776.98   385.5  781.48
   413.2  779.74   512.3  781.53   572.3   785.6   636.3  785.37   768.2  789.84
   780.2  791.04   804.2  797.48   820.2  799.42   836.2  806.57   880.2  819.76
#Mann= 3 , 0 , 0
       0      .1       0   355.2    .045       0   370.2      .1       0
#XS Ineff= 2 , 0
          326.74  790.17  389.49          789.67
Permanent Ineff=
       F       F
Bank Sta=355.2,370.2
XS Rating Curve= 0 ,0
Exp/Cntr=0.3,0.1

Type RM Length L Ch R = 1 ,13355.4 ,285,324.9,365
XS GIS Cut Line= 5
     1711923.151        406735.9     1712115.859      406725.484
     1712119.331      406437.289     1712228.706      406305.345
     1712235.651      406097.011
#Sta/Elev= 30
       0   881.6    39.4  861.53      63  843.45    70.9  840.89    86.6  839.27
    98.5  834.73   137.8  807.43   145.7   799.1   157.5  782.31   165.4  778.28
   260.1  778.84   287.8  779.74   295.6  781.56   339.1  778.46   390.4  777.12
   402.2  776.21   413.7  777.51   429.9  780.34   449.6  780.14   461.5  782.09
   505.1  781.95   521.1  786.52     533  788.06   719.4  790.81   770.6  792.93
   790.2  794.97     802   798.8   813.8  800.43   833.5  811.32     861  820.82
#Mann= 3 , 0 , 0
       0      .1       0   390.4    .045       0   413.7      .1       0
#XS Ineff= 2 , 0
          293.39  789.33
Permanent Ineff=
       F       F
Bank Sta=390.4,413.7
XS Rating Curve= 0 ,0
Exp/Cntr=0.3,0.1

Type RM Length L Ch R = 1 ,13030.5 ,258.7,254.8,250.8
XS GIS Cut Line= 3
     1711901.623      406755.605     1712203.272      406794.668
     1712426.796      406844.581
#Sta/Elev= 30
       0  891.48    15.8  886.09    47.4  871.34    71.1  857.91      83  847.46
    90.9  842.71    98.8  839.98   114.6  837.81   130.4  830.88   150.1  815.97
     162  809.41   169.9  803.94   197.5  778.24   201.5  776.88   213.3  777.38
     237  776.54   268.6   778.4   286.5  774.06   292.3  773.51   301.5  773.95
     316  777.45   359.4  776.85   363.4  777.59   383.1  784.95   410.8  800.21
   426.6  811.72   442.4  821.41     470  834.41   501.6   851.7   533.2   867.6
#Mann= 3 , 0 , 0
       0      .1       0   286.5    .045       0   301.5      .1       0
Bank Sta=286.5,301.5
XS Rating Curve= 0 ,0
Exp/Cntr=0.3,0.1

Type RM Length L Ch R = 1 ,12775.7 ,279.5,283.3,284.6
XS GIS Cut Line= 3
     1711751.582      407060.373     1712160.731       407040.59
     1712577.478      407038.382
#Sta/Elev= 30
       0  940.91    19.9  926.79    67.6  898.01   111.4  882.21   147.2  876.12
     175  866.86   262.5  818.88   282.4  813.08   298.3  803.56   326.1  790.63
     346  776.39   373.8  775.76   397.7  772.44   409.6  772.04   417.1  773.08
   433.4  777.08   453.3  775.73   465.2  778.55   473.1  783.44   500.9  806.28
   532.7  825.96   556.5  837.42   592.2  849.93   667.6  890.64   687.5  896.61
   719.2  910.72   778.8  949.32   794.6  962.56   814.5  969.55   826.4  980.32
#Mann= 3 , 0 , 0
       0      .1       0   397.7    .045       0   417.1      .1       0
Bank Sta=397.7,417.1
XS Rating Curve= 0 ,0
Exp/Cntr=0.3,0.1

Type RM Length L Ch R = 1 ,12492.4 ,316.2,316.7,317.2
XS GIS Cut Line= 3
     1711745.162      407275.752     1712151.189      407315.501
     1712562.425      407348.007
#Sta/Elev= 30
       0  937.67      12  930.07      24  924.42      40  913.36      80  892.35
     108  882.07     124  878.77     132  875.71     168  856.97     184  847.52
     220  830.37     256  811.21     280  802.28     312  787.51     332  781.23
     352  772.88     388  774.01     400  770.79   411.9  770.16   416.8  771.02
   435.7  774.52   479.4  803.67   503.2  818.21   558.7  845.07   582.5  858.05
   622.2  881.81   634.1  885.04     646  892.31   685.6  911.13   820.5  998.34
#Mann= 3 , 0 , 0
       0      .1       0     400    .045       0   416.8      .1       0
Bank Sta=400,416.8
XS Rating Curve= 0 ,0
Exp/Cntr=0.3,0.1

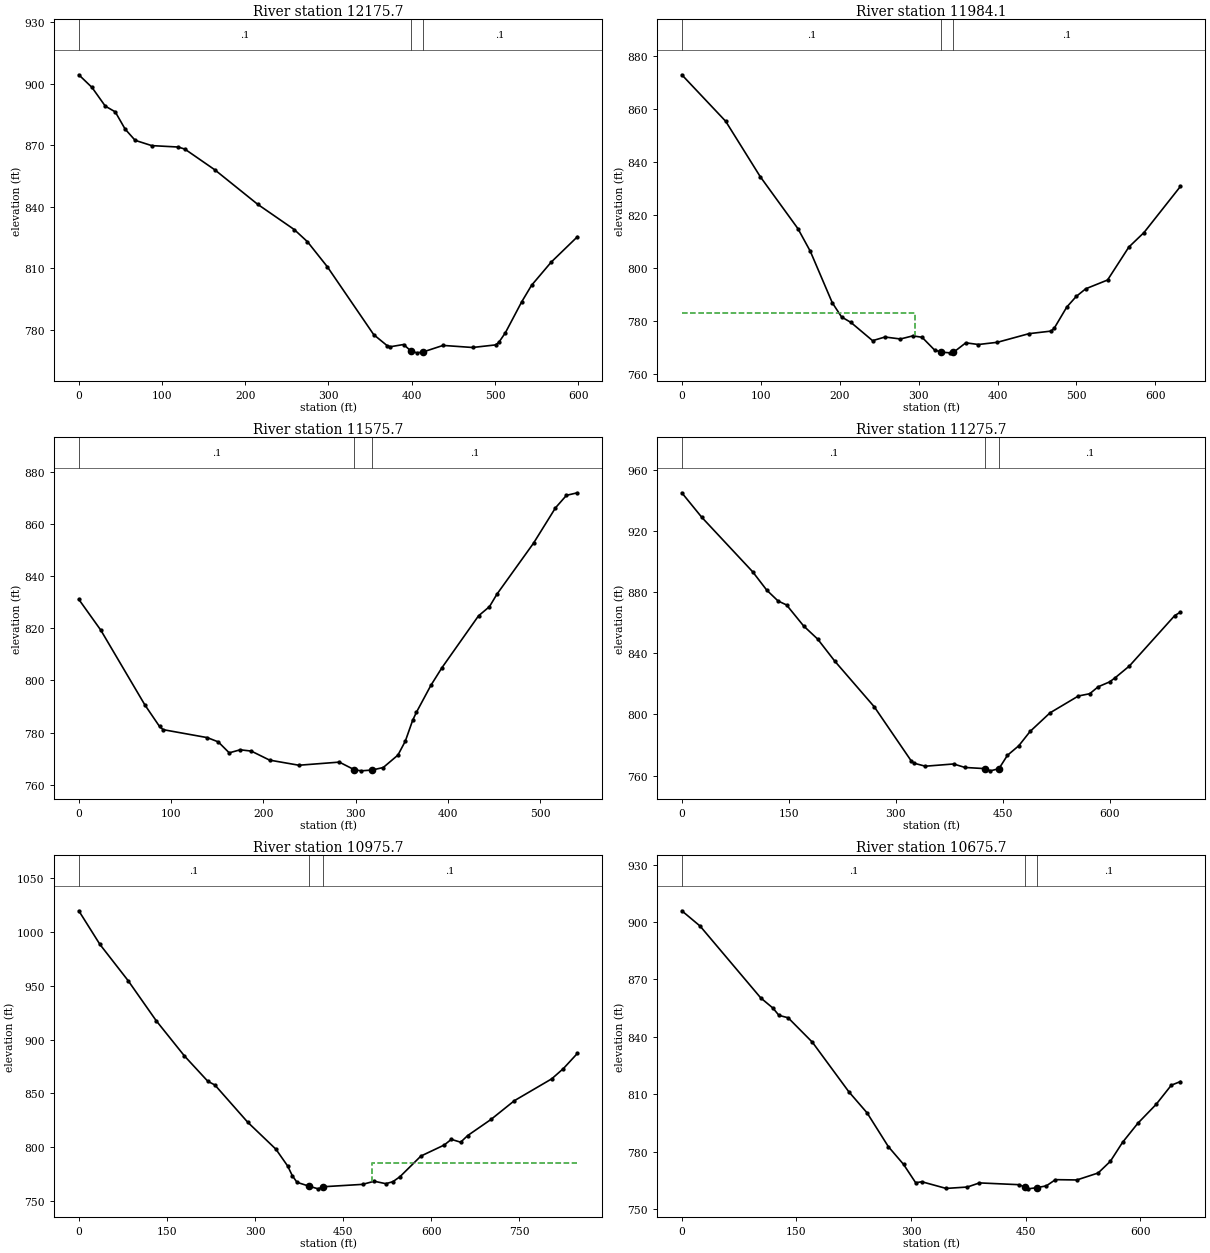
Type RM Length L Ch R = 1 ,12175.7 ,197.3,191.6,185.7
XS GIS Cut Line= 3
     1711694.508      407569.591     1712098.457      407611.683
     1712290.078      407634.511
#Sta/Elev= 30
       0  904.34    15.9  898.15    31.8  889.06    43.8  886.25    55.7  877.83
    67.7  872.37    87.6  869.79   119.4   869.1   127.4  868.09   163.2  858.05
     215  841.14   258.8  828.86   274.7  822.92   298.6   810.7   354.4  777.55
   370.3  772.27   374.3  771.68   390.2  772.77   398.6  769.77   406.1  768.71
   413.6  769.13   437.6  772.33   473.1  771.32   500.7  772.58   504.6   773.8
   512.5   778.5   532.2  793.65     544  801.67   567.6  812.98   599.1  825.36
#Mann= 3 , 0 , 0
       0      .1       0   398.6    .045       0   413.6      .1       0
Bank Sta=398.6,413.6
XS Rating Curve= 0 ,0
Exp/Cntr=0.3,0.1

Type RM Length L Ch R = 1 ,11984.1 ,386,408.4,429.8
XS GIS Cut Line= 5
     1711786.605      407747.359     1711962.387      407821.143
     1712105.616      407797.272     1712298.758       407764.72
     1712348.671      407677.914
#Sta/Elev= 30
       0  872.75    55.6  855.23    99.3   834.4     147  814.84   162.8  806.26
   190.6   786.9   202.4  781.52   214.2  779.48   241.7   772.6   257.4  773.97
     277  773.23   292.7   774.4   304.4  773.87   320.2  769.08   328.9  768.27
   339.8  768.01   343.9  768.14   359.8  771.78   375.8  771.15   399.8  771.98
   439.8  775.23   467.8   776.2   471.8  777.26   487.7  785.24   499.7  789.25
   511.7  792.13   539.4  795.44   566.4  807.86   585.6  813.33   631.8  830.72
#Mann= 3 , 0 , 0
       0      .1       0   328.9    .045       0   343.9      .1       0
#XS Ineff= 2 , 0
          295.99  783.14
Permanent Ineff=
       F       F
Bank Sta=328.9,343.9
XS Rating Curve= 0 ,0
Exp/Cntr=0.3,0.1

Type RM Length L Ch R = 1 ,11575.7 ,305.1,300,294.4
XS GIS Cut Line= 3
     1711825.668       407933.99       1712035.8      408156.608
     1712198.932      408324.615
#Sta/Elev= 30
       0  831.12    23.8  819.32    71.6  790.59    87.5  782.31    91.4  781.09
   139.2  778.04   151.1   776.4     163  772.19   174.9  773.36   186.9  772.86
   206.7   769.4   238.5  767.43   282.3  768.63   298.6  765.69   306.1  765.28
     318   765.6   329.9  766.56   345.8  771.33   353.8  776.69   361.7  784.63
   365.7  787.68   381.5  798.11   393.4  804.84   433.1  824.79     445  828.33
     453  833.08   492.7  852.69   516.5  866.26   528.4  871.06   540.3  872.04
#Mann= 3 , 0 , 0
       0      .1       0   298.6    .045       0     318      .1       0
Bank Sta=298.6,318
XS Rating Curve= 0 ,0
Exp/Cntr=0.3,0.1

Type RM Length L Ch R = 1 ,11275.7 ,298,300,303.9
XS GIS Cut Line= 3
      1711518.05      408163.699     1711880.297      408400.617
     1712107.786      408539.459
#Sta/Elev= 30
       0  945.22    27.8  929.27    99.3  893.51   119.1  881.46     135  874.34
   146.9  871.74   170.8  858.01   190.6  849.35   214.4  835.01     270  804.97
   321.6  769.68   325.6  768.09   341.5   766.1   381.2  767.57   397.1  765.28
   425.3  764.52   432.8  763.07   444.8  764.51   456.7  773.24   472.6   779.5
   488.5  788.89   516.4  801.05   556.2   812.1   572.1  813.58     584  818.14
   599.9  821.32   607.9  824.07   627.8  831.78   691.4  864.81   699.4  867.03
#Mann= 3 , 0 , 0
       0      .1       0   425.3    .045       0   444.8      .1       0
Bank Sta=425.3,444.8
XS Rating Curve= 0 ,0
Exp/Cntr=0.3,0.1

Type RM Length L Ch R = 1 ,10975.7 ,297,300,299.3
XS GIS Cut Line= 3
      1711337.23      408335.613     1711657.317      408581.101
     1711989.921      408877.142
#Sta/Elev= 30
       0 1019.23      36  988.06    83.9  954.56   131.8  917.38   179.7  884.84
   219.7  861.26   231.6  857.89   287.6  823.33   335.5  798.39   355.5  782.82
   363.4  773.87   371.4  767.72   391.4  764.23   407.4  761.68   415.3  763.59
   482.9  765.82   502.8  768.71   522.6  766.45   534.6  768.32   546.5  772.85
   582.3  792.06     622  802.28     634  807.51   649.9  804.88   661.8     811
   701.6  825.97   741.3  843.31   804.9  863.56   824.8  873.09   848.7   887.2
#Mann= 3 , 0 , 0
       0      .1       0   391.4    .045       0   415.3      .1       0
#XS Ineff= 2 , 0
                          499.72          785.36
Permanent Ineff=
       F       F
Bank Sta=391.4,415.3
XS Rating Curve= 0 ,0
Exp/Cntr=0.3,0.1

Type RM Length L Ch R = 1 ,10675.7 ,291,300,308.5
XS GIS Cut Line= 3
     1711214.666      408554.813     1711557.079      408857.944
      1711706.31      408984.338
#Sta/Elev= 30
       0  905.87    23.9  897.89   103.4  860.33   119.3  855.04   127.2  851.24
   139.2  849.98     171  837.19   218.7  811.31   242.6  800.29   270.4  782.67
   290.3  773.41   306.2   763.8   314.2  764.33     346  760.84   373.8  761.56
   389.7  763.72   441.4  762.79   449.8  761.46   453.3  760.62   464.8  761.23
   477.3  762.18   489.2  765.42   517.2  765.26   545.1   768.9   561.1  775.01
     577  784.87     597  794.84     621  804.73   640.9  814.76   652.9  816.67
#Mann= 3 , 0 , 0
       0      .1       0   449.8    .045       0   464.8      .1       0
Bank Sta=449.8,464.8
XS Rating Curve= 0 ,0
Exp/Cntr=0.3,0.1