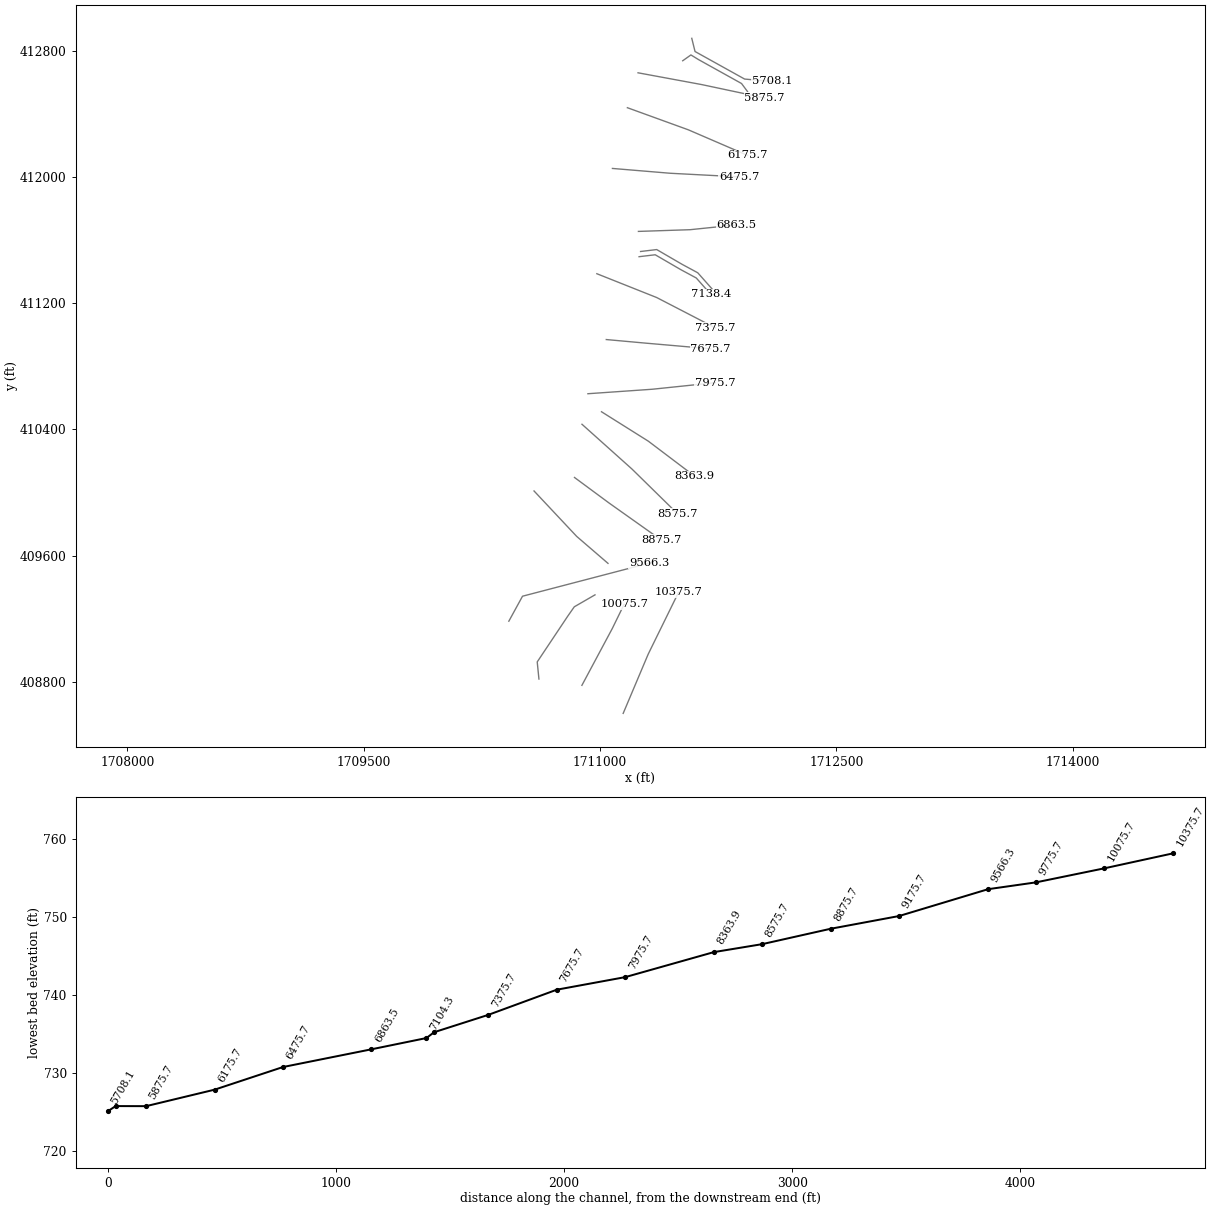
HEC-RAS study BGHORSECK.prj: BGHORSECK

--- BGHORSECK.g01 (geometry) --- (continued)

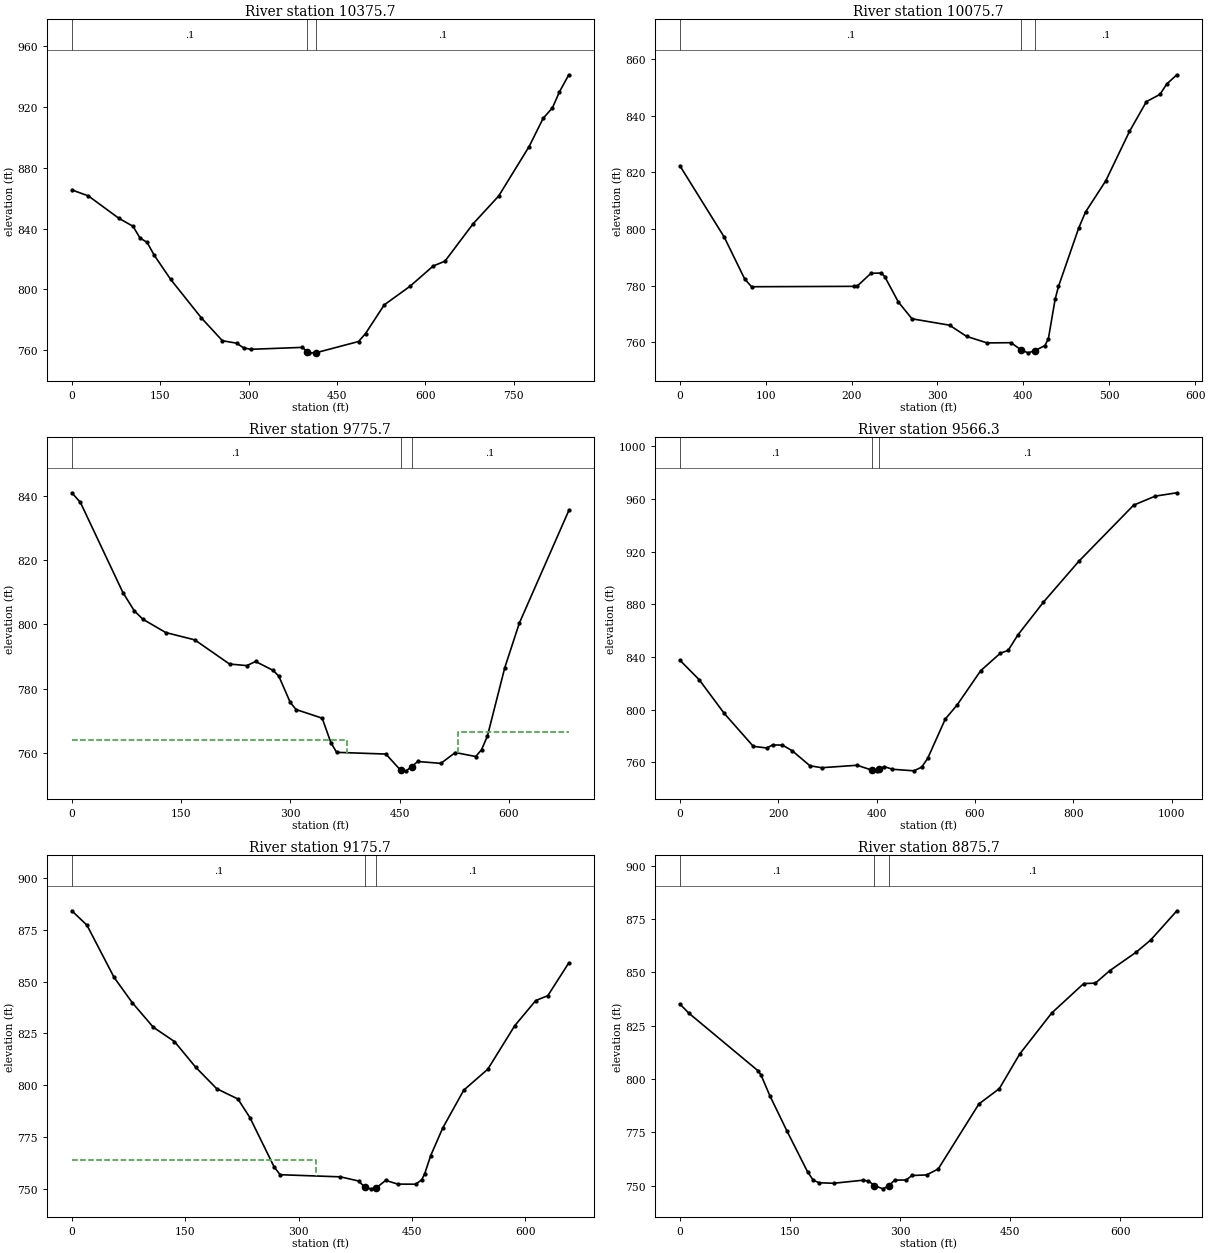
Type RM Length L Ch R = 1 ,10375.7 ,301.3,300,299.5
XS GIS Cut Line= 3
     1711147.345      408599.435     1711305.972      408974.692
      1711498.38      409366.377
#Sta/Elev= 30
       0  865.41      28  861.49    79.9  846.72   103.8  841.49   115.8  833.74
   127.8  830.86   139.8  822.46   167.8  806.49   219.7  781.24   255.6  766.11
   279.6  764.49   291.6  761.42   303.6  760.44   391.4  761.72   399.9  758.77
   403.4  758.12   414.9  758.22   486.8  765.58   498.6  770.81   530.4   789.7
     574  801.91   613.7  815.36   633.5  818.48   681.1  843.03   724.8  861.45
   776.4  894.01   800.2  912.56     816  919.49   827.9  930.03   843.8  941.25
#Mann= 3 , 0 , 0
       0      .1       0   399.9    .045       0   414.9      .1       0
Bank Sta=399.9,414.9
XS Rating Curve= 0 ,0
Exp/Cntr=0.3,0.1

Type RM Length L Ch R = 1 ,10075.7 ,302.3,300,296.5
XS GIS Cut Line= 3
     1710885.365      408777.225     1711078.508      409138.181
     1711152.925      409290.327
#Sta/Elev= 30
       0  822.38    51.7  797.11    75.5  782.31    83.5  779.59   202.7  779.73
   206.7  779.89   222.6  784.35   234.5  784.44   238.5  783.21   254.4   774.2
   270.3  768.25     314  765.99   333.9  762.03   357.7  759.72   385.5   759.8
   397.5  757.23   405.4  756.21   413.3  756.96   425.1  758.78   429.1  761.15
     437  775.18   440.9  779.69   464.5  800.39   472.4  806.01     496  817.08
   523.6  834.53   543.3  845.07   559.1  847.61   566.9  851.28   578.8  854.56
#Mann= 3 , 0 , 0
       0      .1       0   397.5    .045       0   413.3      .1       0
Bank Sta=397.5,413.3
XS Rating Curve= 0 ,0
Exp/Cntr=0.3,0.1

Type RM Length L Ch R = 1 ,9775.7  ,225.8,209.4,193.1
XS GIS Cut Line= 5
      1710612.56      408817.237      1710601.71      408925.744
     1710795.988      409216.635     1710836.969      409275.168
     1710968.463      409351.091
#Sta/Elev= 30
       0  841.01    11.7  838.04    70.1  809.94    85.7  804.26    97.4  801.64
   128.9  797.48   168.7   795.2   216.4  787.68   240.2  787.18   252.2  788.47
     276  785.72     284  783.94   299.8   775.7   307.8   773.5   343.6  770.81
   355.5  763.22   363.4  760.17     431  759.64   451.4  754.56   458.8  754.41
   466.4  755.71   474.7  757.32   506.5  756.74   526.3  760.11   554.3  758.87
   562.3  760.98   570.3  765.19   594.2  786.54   614.2  800.43   682.1   835.5
#Mann= 3 , 0 , 0
       0      .1       0   451.4    .045       0   466.4      .1       0
#XS Ineff= 2 , 0
          378.29  764.14  529.85          766.43
Permanent Ineff=
       F       F
Bank Sta=451.4,466.4
XS Rating Curve= 0 ,0
Exp/Cntr=0.3,0.1

Type RM Length L Ch R = 1 ,9566.3  ,414.7,390.6,367.6
XS GIS Cut Line= 3
     1710421.588       409183.99     1710508.394      409342.411
     1711311.315      409552.007
#Sta/Elev= 30
       0  837.58    39.3  822.72    90.3  797.11   149.2  772.17   176.7  770.89
   188.6  773.23   208.6  773.08   228.5  768.76   264.4  757.39   288.4  755.91
   360.2  757.78   390.2  754.11   400.1  753.54   405.2  754.97     416  756.73
     432  754.74   475.9  753.55   491.8  756.42   503.8  763.03   539.7  792.96
   563.6  803.54   611.5  829.57   651.4  842.85   667.4  845.04   687.3  856.82
   739.2  881.68     811  912.66   922.7  955.38   966.6   962.2  1010.5  964.74
#Mann= 3 , 0 , 0
       0      .1       0   390.2    .045       0   405.2      .1       0
Bank Sta=390.2,405.2
XS Rating Curve= 0 ,0
Exp/Cntr=0.3,0.1

Type RM Length L Ch R = 1 ,9175.7  ,295.7,300,302.1
XS GIS Cut Line= 3
     1710581.454      410009.868     1710852.204      409721.724
     1711050.928      409550.744
#Sta/Elev= 30
       0  884.15      20  877.21    55.9  852.04    79.9  839.88   107.8     828
   135.8  821.11   163.8  808.75   191.7  798.37   219.7  793.42   235.6  784.45
   267.6  760.69   275.6  756.91   355.4  755.88   379.4  753.88   387.9  750.79
   395.4   750.1   402.9  750.59   415.2  754.18   431.1  752.39     455  752.33
   462.9  754.48   466.9  757.46   474.8  766.15   490.7  779.43   518.5  797.68
   550.3  807.78     586  828.77   613.8  840.89   629.7  843.22   657.5  859.04
#Mann= 3 , 0 , 0
       0      .1       0   387.9    .045       0   402.9      .1       0
#XS Ineff= 2 , 0
          323.29     764
Permanent Ineff=
       F       F
Bank Sta=387.9,402.9
XS Rating Curve= 0 ,0
Exp/Cntr=0.3,0.1

Type RM Length L Ch R = 1 ,8875.7  ,302.3,300,296.1
XS GIS Cut Line= 3
     1710838.255      410095.449     1711057.473      409933.588
     1711387.361      409699.925
#Sta/Elev= 30
       0  835.18    11.8  830.97   106.6   803.8   110.6  801.77   122.4  792.22
   146.1  775.38   173.8   756.5   181.7  752.48   189.6  751.33   209.3  751.08
   248.8   752.5   256.7  752.15     265  750.01   276.5  748.47   284.4  749.87
   292.3  752.52   308.2  752.64   316.1  754.73   335.9  754.98   351.8  757.81
   407.2  788.29     435  795.47   462.7  811.69   506.3  830.93   549.9  844.75
   565.8  844.95   585.6  850.86   621.3  859.45   641.1  865.16   676.8  878.89
#Mann= 3 , 0 , 0
       0      .1       0     265    .045       0   284.4      .1       0
Bank Sta=265,284.4
XS Rating Curve= 0 ,0
Exp/Cntr=0.3,0.1

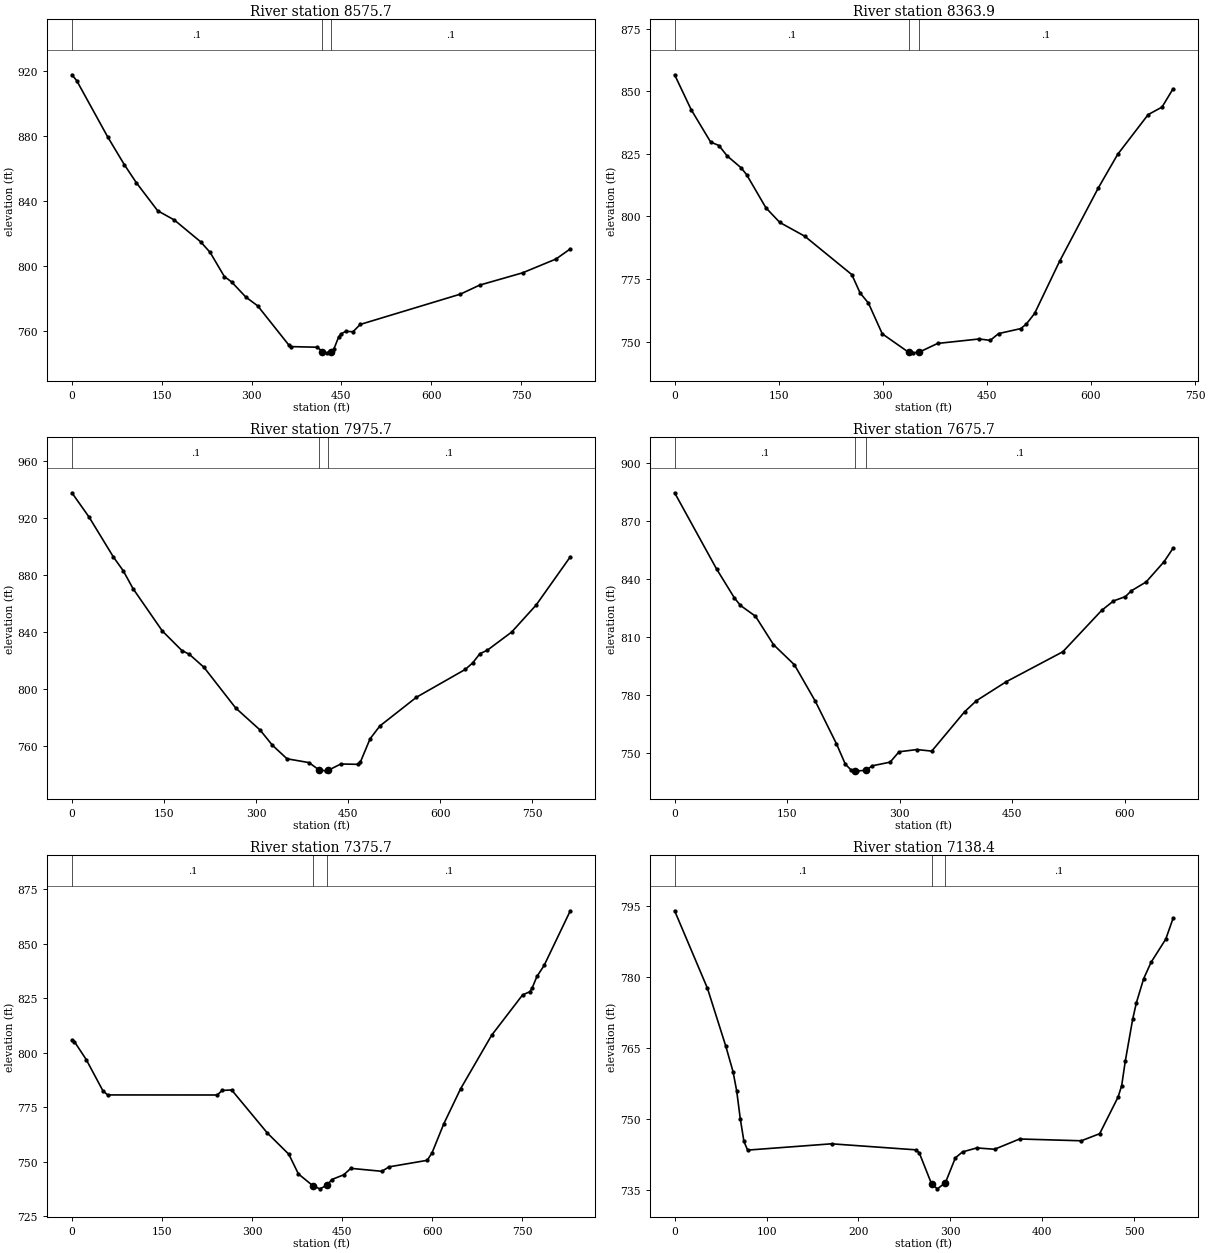
Type RM Length L Ch R = 1 ,8575.7  ,207.7,211.8,213.6
XS GIS Cut Line= 3
     1710885.795      410432.798     1711202.936       410149.01
     1711493.379      409864.373
#Sta/Elev= 30
       0  917.87       8  914.27    59.7  879.62    87.5   862.5   107.4  851.46
   143.2  834.08     171  828.38   214.8  814.99   230.7  808.45   254.6   793.5
   266.5  790.27   290.4  780.87   310.2  775.47   361.9  751.45   365.9  750.34
   409.7  749.95   418.1  747.32   425.6   746.5   433.1   747.1   437.5  748.92
   445.5  756.35   449.5  758.22   457.5  759.76   469.4  759.49   481.4     764
   648.8  782.69   680.7  788.22   752.5  795.81   808.3  804.32   832.2  810.56
#Mann= 3 , 0 , 0
       0      .1       0   418.1    .045       0   433.1      .1       0
Bank Sta=418.1,433.1
XS Rating Curve= 0 ,0
Exp/Cntr=0.3,0.1

Type RM Length L Ch R = 1 ,8363.9  ,373.7,388.2,405.7
XS GIS Cut Line= 3
     1711009.696      410512.115     1711307.005      410325.484
     1711599.973      410104.129
#Sta/Elev= 30
       0  856.58    23.9  842.61    51.9   829.7    63.8  828.32    75.8  824.13
    95.7  819.44   103.7  816.68   131.6   803.4   151.6  797.57   187.5  792.08
   255.3  776.74   267.3  769.39   279.2  765.39   299.2  753.08   337.5  745.64
     343  745.48   352.5  745.77     379  749.24   438.8  751.02   454.8  750.47
   466.8  753.17   498.7  755.16   506.7  756.95   518.7   761.2   554.6  781.99
   610.5  811.36   638.4  824.78   682.3  840.65   702.3  843.67   718.2  850.95
#Mann= 3 , 0 , 0
       0      .1       0   337.5    .045       0   352.5      .1       0
Bank Sta=337.5,352.5
XS Rating Curve= 0 ,0
Exp/Cntr=0.3,0.1

Type RM Length L Ch R = 1 ,7975.7  ,303.6,300,295.6
XS GIS Cut Line= 3
     1710923.494      410626.458     1711332.732      410654.931
     1711732.352      410696.577
#Sta/Elev= 30
       0  937.87    27.9  920.83    67.7  892.65    83.6  883.04    99.6  870.45
   147.4  840.62   179.2   826.9   191.2   824.3   215.1  815.13   266.8   786.5
   306.7  770.94   326.6  760.31   350.5  750.76   386.3  748.07   402.7  742.89
   414.2  742.28   417.7  742.67   438.1   747.1   465.9  746.85   469.9  748.36
   485.8  764.82   501.7  773.82   561.4  794.06     641  813.64   652.9   818.2
   664.8   824.7   676.8  827.11   716.5  839.91   756.3  858.88     812  892.83
#Mann= 3 , 0 , 0
       0      .1       0   402.7    .045       0   417.7      .1       0
Bank Sta=402.7,417.7
XS Rating Curve= 0 ,0
Exp/Cntr=0.3,0.1

Type RM Length L Ch R = 1 ,7675.7  ,306.5,300,291.1
XS GIS Cut Line= 3
     1711040.078      410970.015     1711286.608      410947.599
      1711701.97      410911.421
#Sta/Elev= 30
       0   884.5    55.9  845.09    79.8  830.05    87.8  826.21   107.8  820.63
   131.8  805.95   159.7  795.53   187.7  776.58   215.6  754.79   227.6  744.11
   235.6  740.97     240  740.73   243.6  740.67     255  740.89   263.4  743.26
   287.3  745.17   299.2  750.52     323  751.68   342.8  750.87   386.5  771.18
   402.4  776.96   442.1  786.76   517.6  802.27   569.2  823.61   585.1  828.54
     601  830.81   608.9  833.78   628.7  838.39   652.6  848.88   664.5  855.81
#Mann= 3 , 0 , 0
       0      .1       0     240    .045       0     255      .1       0
Bank Sta=240,255
XS Rating Curve= 0 ,0
Exp/Cntr=0.3,0.1

Type RM Length L Ch R = 1 ,7375.7  ,240.4,237.3,236.2
XS GIS Cut Line= 3
     1710980.191      411387.503     1711360.086      411236.404
     1711734.082      411043.108
#Sta/Elev= 30
       0  805.79       4   805.1    23.8  796.84    51.6  782.49    59.5  780.57
   242.1  780.54   250.1  782.63     266  782.85   325.5  763.05   361.2  753.32
   377.1   744.3   401.3  738.84   412.8  737.45   424.7  739.08   432.7  741.72
   452.5  743.88   464.4  746.86   516.1   745.5     528  747.54   591.5  750.54
   599.5  753.92   619.3  767.38   647.1  783.36   698.8  807.96   750.4  826.51
   762.3  827.94   766.3  829.67   774.2  834.96   786.2  840.02   829.8  865.13
#Mann= 3 , 0 , 0
       0      .1       0   401.3    .045       0   424.7      .1       0
Bank Sta=401.3,424.7
XS Rating Curve= 0 ,0
Exp/Cntr=0.3,0.1

Type RM Length L Ch R = 1 ,7138.4  ,33.9,34.1,34.3
XS GIS Cut Line= 5
     1711248.151      411495.449     1711350.617      411507.663
     1711512.039      411413.852     1711611.149      411360.439
      1711703.88      411255.865
#Sta/Elev= 30
       0  794.02    35.7  777.63    55.6  765.43    63.5  760.03    67.5  755.95
    71.4  750.07    75.4  745.24    79.4  743.42   170.7  744.75   262.1  743.48
   266.1  742.85   279.6  736.23   285.9  735.23   294.6  736.54   305.4  741.78
   313.2  743.04   328.7  743.88   348.1   743.6   375.3  745.77   442.4  745.39
   462.4  746.89   482.4  754.63   486.3  757.02   490.3  762.28   498.3   771.1
   502.3  774.56   510.3  779.69   518.3  783.12   534.3  788.03   542.2   792.4
#Mann= 3 , 0 , 0
       0      .1       0   279.6    .045       0   294.6      .1       0
Bank Sta=279.6,294.6
XS Rating Curve= 0 ,0
Exp/Cntr=0.3,0.1

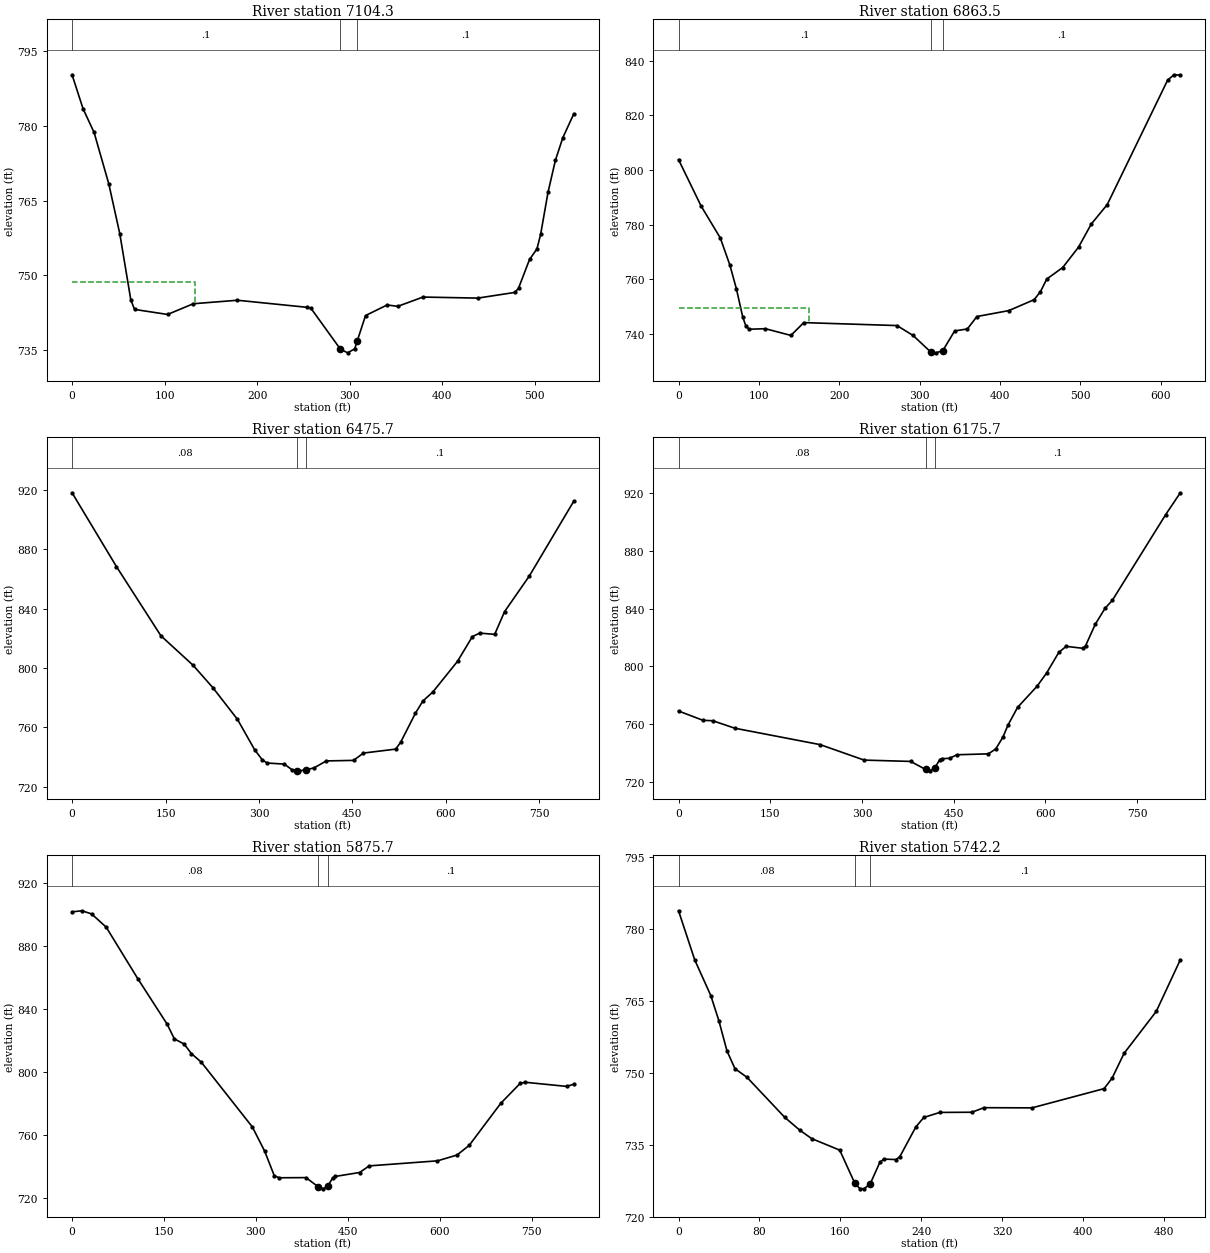
Type RM Length L Ch R = 1 ,7104.3  ,228.6,240.8,253.5
XS GIS Cut Line= 5
     1711257.699      411528.435     1711360.165      411540.649
     1711521.588      411446.838     1711620.698      411393.425
     1711713.428      411288.852
#Sta/Elev= 30
       0  790.26    11.9  783.43    23.8  778.69    39.7  768.36    51.6  758.34
    63.5  745.08    67.5  743.19   103.2  742.18     131  744.33   178.7  745.03
   254.1  743.61   258.1  743.42   289.9  735.23   297.7  734.48   305.4  735.28
   308.2  736.91   317.1  741.96   340.4  744.08     352  743.81   379.2  745.67
   438.4  745.46   478.4   746.6   482.4  747.44   494.3  753.21   502.3  755.32
   506.3  758.24   514.3  766.71   522.3  773.13   530.3  777.65   542.2  782.45
#Mann= 3 , 0 , 0
       0      .1       0   289.9    .045       0   308.2      .1       0
#XS Ineff= 2 , 0
          132.96  748.75
Permanent Ineff=
       F       F
Bank Sta=289.9,308.2
XS Rating Curve= 0 ,0
Exp/Cntr=0.3,0.1

Type RM Length L Ch R = 1 ,6863.5  ,390.1,387.8,384.7
XS GIS Cut Line= 3
     1711244.071      411655.779     1711571.762      411666.629
     1711866.901      411697.011
#Sta/Elev= 30
       0   803.8      28  786.85      52   775.1      64   765.1      72  756.51
      80  746.06      84  742.73      88  741.68     108  741.88   139.9  739.42
   155.9  744.11   271.9  743.03   291.9  739.41   313.8  733.38   319.9  733.04
   328.8  733.77   343.7  741.07   359.5  741.78   371.4  746.34     411   748.5
   442.6   752.5   450.5  755.44   458.4  760.08   478.2  764.28     498   771.8
   513.8  780.23   533.6  787.32   608.8  832.91   616.7  834.87   624.6  834.76
#Mann= 3 , 0 , 0
       0      .1       0   313.8    .045       0   328.8      .1       0
#XS Ineff= 2 , 0
          161.84  749.57
Permanent Ineff=
       F       F
Bank Sta=313.8,328.8
XS Rating Curve= 0 ,0
Exp/Cntr=0.3,0.1

Type RM Length L Ch R = 1 ,6475.7  ,305.9,300,291.7
XS GIS Cut Line= 3
      1711079.14      412055.084     1711446.272      412024.511
     1711882.681      412001.736
#Sta/Elev= 30
       0  917.89    71.3  868.18   142.6  821.65   194.1  801.87   225.8  786.84
   265.4  765.46   293.1  744.92     305  738.36   312.9  736.03   340.7  735.31
   352.6  731.62   360.9   730.9   364.4  730.77   375.9  731.51   388.3  732.74
   408.1  737.45   451.8   737.8   467.7  742.73   519.4  745.39   527.3  749.93
   551.2  769.62   563.1  777.77     579   783.8   618.7  804.48   642.5  821.13
   654.4  823.46   678.3   822.6   694.2  837.92   733.9  861.88   805.4  912.33
#Mann= 3 , 0 , 0
       0     .08       0   360.9    .045       0   375.9      .1       0
Bank Sta=360.9,375.9
XS Rating Curve= 0 ,0
Exp/Cntr=0.3,0.1

Type RM Length L Ch R = 1 ,6175.7  ,296.1,300,304.4
XS GIS Cut Line= 3
      1711173.96      412440.223     1711560.854      412300.027
     1711936.562      412138.008
#Sta/Elev= 30
       0  769.22      40  762.78    55.9   762.5    91.9  757.34   231.7  745.97
   303.6  735.29   379.6  734.38     404  728.85   411.5  727.87     419  729.95
   427.4  735.64   431.4  736.29   443.3  736.51   455.2  738.98   506.8  739.61
   518.8  742.98   530.7  751.26   538.6  759.28   554.5  771.72   586.3  786.28
   602.2   795.6     622  809.75     634   813.9   661.8  812.53   665.7  814.28
   681.6  829.15   697.5  840.17   709.4  845.63   796.8  904.97   820.7  920.02
#Mann= 3 , 0 , 0
       0     .08       0     404    .045       0     419      .1       0
Bank Sta=404,419
XS Rating Curve= 0 ,0
Exp/Cntr=0.3,0.1

Type RM Length L Ch R = 1 ,5875.7  ,140.8,133.5,126.6
XS GIS Cut Line= 3
     1711241.549      412661.578     1711644.343      412587.164
     1712044.942      412502.257
#Sta/Elev= 30
       0  901.62    15.9  902.31    31.8  900.34    55.7  891.91   107.4  859.12
   155.1  830.37     167  820.96   182.9   817.7   194.9  811.58   210.8  806.25
   294.3  765.04   314.2  749.83   330.1   734.1     338  732.79   381.8  732.88
   402.1  726.98   409.6  725.76   417.1  727.34   425.5  732.75   429.5  733.63
   469.2  736.13   485.2  740.34   596.5  743.54   628.3   747.2   648.2  753.33
   699.8  780.07   731.6  792.77   739.6  793.43   807.2   790.8   819.1  792.18
#Mann= 3 , 0 , 0
       0     .08       0   402.1    .045       0   417.1      .1       0
Bank Sta=402.1,417.1
XS Rating Curve= 0 ,0
Exp/Cntr=0.3,0.1

Type RM Length L Ch R = 1 ,5742.2  ,34.1,34.1,34.1
XS GIS Cut Line= 5
     1711525.212      412738.005     1711577.295      412774.898
     1711625.039      412745.601     1711898.476      412593.691
     1711936.453      412542.693
#Sta/Elev= 30
       0  783.74      16  773.51    31.9  766.06    39.9  760.81    47.9  754.53
    55.8  750.82    67.6  749.04   104.9   740.7   119.8  738.01   131.7  736.24
   159.4  733.84   174.4  726.89   179.2  725.84   183.2  725.77   189.4  726.74
     199  731.27     203  731.98   214.9  731.87   218.8  732.47   234.7  738.69
   242.6  740.66   258.4   741.7   290.1  741.74     302  742.69   349.5  742.65
   420.8  746.66   428.7  748.83   440.6  754.03   472.4  762.76   496.2  773.53
#Mann= 3 , 0 , 0
       0     .08       0   174.4    .045       0   189.4      .1       0
Bank Sta=174.4,189.4
XS Rating Curve= 0 ,0
Exp/Cntr=0.3,0.1

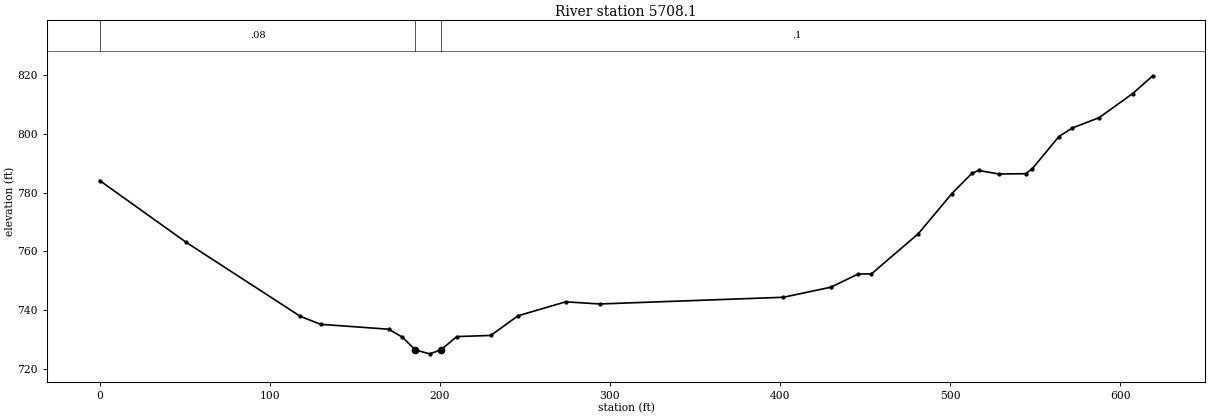
Type RM Length L Ch R = 1 ,5708.1  ,133.6,132.4,130.4
XS GIS Cut Line= 4
     1711582.721      412880.149     1711603.337      412796.599
     1711918.007      412621.903     1712090.533      412606.712
#Sta/Elev= 30
       0  784.13    50.8  763.12     118  737.88     130  735.16     170  733.49
     178  730.79   185.6  726.44     194  725.11   200.6  726.44     210  730.98
     230  731.38     246  738.07     274  742.82     294  742.09     402  744.37
     430  747.81     446   752.3   453.8  752.33   481.4  766.04   501.1  779.69
   512.9  786.59   516.8  787.54   528.6  786.36   544.4  786.44   548.3  788.09
     564   799.1   571.9  802.02   587.7  805.53   607.4  813.74   619.2  819.79
#Mann= 3 , 0 , 0
       0     .08       0   185.6    .045       0   200.6      .1       0
Bank Sta=185.6,200.6
XS Rating Curve= 0 ,0
Exp/Cntr=0.3,0.1