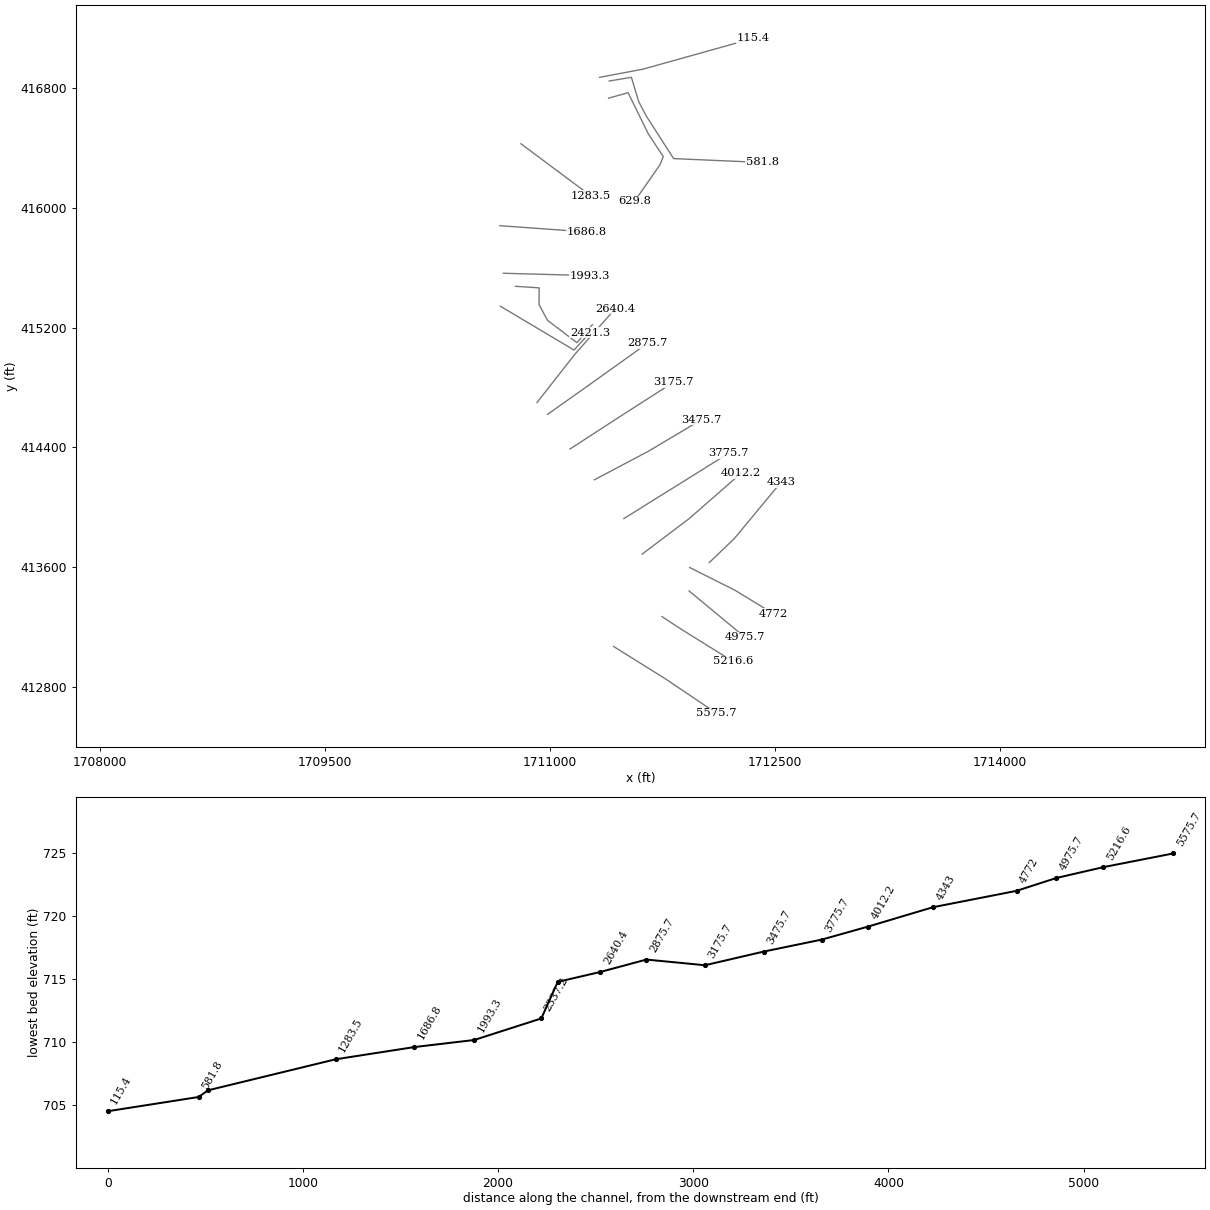
HEC-RAS study BGHORSECK.prj: BGHORSECK

--- BGHORSECK.g01 (geometry) --- (continued)

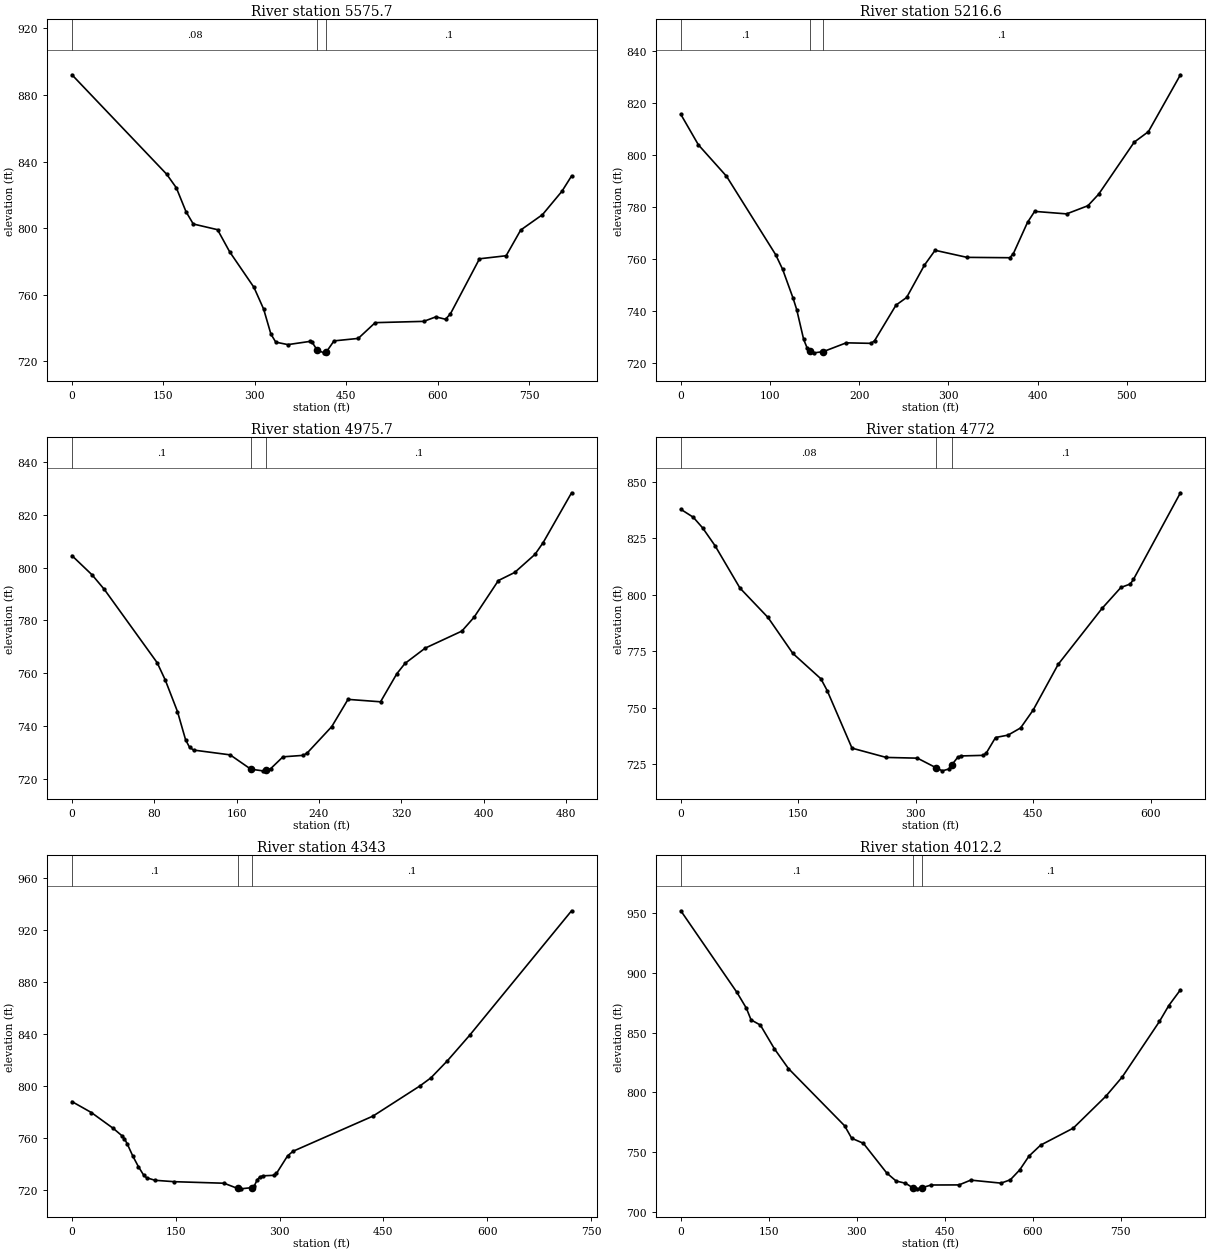
Type RM Length L Ch R = 1 ,5575.7  ,359.7,359.1,359.6
XS GIS Cut Line= 3
      1711425.24      413070.348     1711772.618      412852.945
     1712111.949      412623.813
#Sta/Elev= 30
       0  892.14   155.2   832.4   171.1  824.21     187  809.84   198.9  802.43
   238.7  799.01   258.6   785.7   298.4  764.35   314.3  751.26   326.2  736.25
   334.2  731.39   354.1  729.92   389.9  731.83   393.9  731.32   402.3  726.44
   413.8  724.97   417.3  725.64   429.7  732.16   469.4  733.64   497.2  743.12
   576.8  743.89   596.6  746.59   612.5  745.16   620.5  748.37   668.2  781.51
   711.9  783.35   735.8   798.8   771.5  808.05   803.4   822.1   819.2  831.32
#Mann= 3 , 0 , 0
       0     .08       0   402.3    .045       0   417.3      .1       0
Bank Sta=402.3,417.3
XS Rating Curve= 0 ,0
Exp/Cntr=0.3,0.1

Type RM Length L Ch R = 1 ,5216.6  ,242.9,240.9,237.6
XS GIS Cut Line= 3
     1711747.543      413270.362     1711875.581      413185.727
     1712220.633      412970.883
#Sta/Elev= 30
       0  815.65    19.7  803.92    51.2  791.84   106.3  761.66   114.1  756.03
   125.9  744.84   129.9  740.51   137.7  729.02   141.7  725.66   144.8  724.44
   149.6  723.88   159.8  724.36   185.4  727.73   213.3  727.53   217.2  728.57
   241.2  742.25   253.1  745.18     273  757.59     285  763.34   320.8  760.62
   368.7  760.48   372.7  762.03   388.6  774.09   396.6  778.31   432.4  777.35
   456.3  780.49   468.3  784.91   508.2  804.96   524.1  808.99     560  830.88
#Mann= 3 , 0 , 0
       0      .1       0   144.8    .045       0   159.8      .1       0
Bank Sta=144.8,159.8
XS Rating Curve= 0 ,0
Exp/Cntr=0.3,0.1

Type RM Length L Ch R = 1 ,4975.7  ,198.9,203.8,207.4
XS GIS Cut Line= 3
     1711927.664      413441.803     1712067.229      413326.047
     1712300.928      413131.473
#Sta/Elev= 30
       0  804.56    19.7  797.22    31.5  791.74    82.8  763.98    90.7  757.39
   102.5   745.5   110.4  734.78   114.3   731.9   118.2  730.89   153.7  729.07
   173.8  723.64   185.3  723.02   188.8  723.23   193.2   723.9     205  728.33
   224.8  728.89   228.7  729.85   252.4  739.78   268.2   750.1   299.8  749.18
   315.6   759.8   323.5   763.7   343.2  769.52   378.8  775.97   390.6  781.18
   414.3  795.13   430.1  798.18   449.9  805.06   457.8  809.51   485.4  828.38
#Mann= 3 , 0 , 0
       0      .1       0   173.8    .045       0   188.8      .1       0
Bank Sta=173.8,188.8
XS Rating Curve= 0 ,0
Exp/Cntr=0.3,0.1

Type RM Length L Ch R = 1 ,4772    ,400.5,429,460.8
XS GIS Cut Line= 3
     1711932.005      413598.053     1712233.654      413446.143
      1712489.73      413289.893
#Sta/Elev= 30
       0  837.88    15.9  834.36    27.8  829.66    43.7  821.74    75.5  802.97
   111.3  789.94     143  774.02   178.8  762.78   186.8  757.57   218.5  732.05
   262.2  727.94     302  727.62     326  723.33   333.8     722   341.7  722.77
   345.7  724.57   353.7  728.12   357.7   728.6   385.7  728.86   389.7  729.77
   401.7  736.77   417.7  737.83   433.7  741.02   449.7  748.92   481.7  769.21
   537.7  793.99   561.7  803.24   573.7  804.79   577.7   806.8   637.7   845.2
#Mann= 3 , 0 , 0
       0     .08       0     326    .045       0   345.7      .1       0
Bank Sta=326,345.7
XS Rating Curve= 0 ,0
Exp/Cntr=0.3,0.1

Type RM Length L Ch R = 1 ,4343    ,333.3,330.8,327.5
XS GIS Cut Line= 3
     1712062.213      413630.605     1712229.314      413791.195
     1712541.814        414168.8
#Sta/Elev= 30
       0  787.91      28  779.49    59.9  767.18    71.9  761.75    75.9  759.26
    79.9  755.29    87.9  745.98    95.9   737.9   103.9  731.01   107.9  729.25
   119.9  727.29   147.8  726.21   219.8  725.02   239.3  721.01   243.7   720.7
   259.6  721.61   263.6  723.18   267.6  727.54   271.6  729.88   275.6  730.71
   291.5  731.12   295.5  732.56   311.5  746.07   319.4  749.63     435  776.75
   502.7  799.94   518.7  806.21   542.6  819.43   574.5  838.92   721.9  934.89
#Mann= 3 , 0 , 0
       0      .1       0   239.3    .045       0   259.6      .1       0
Bank Sta=239.3,259.6
XS Rating Curve= 0 ,0
Exp/Cntr=0.3,0.1

Type RM Length L Ch R = 1 ,4012.2  ,239.1,236.5,232.8
XS GIS Cut Line= 3
     1711614.806      413687.169     1711929.835      413925.744
     1712273.672      414226.804
#Sta/Elev= 30
       0   951.9    95.8  883.54   111.8  870.37   119.8  860.59   135.7  856.24
   159.7  836.33   183.6  819.83   279.4  771.94   291.4  761.54   311.4  757.27
   351.3   732.4   367.2  725.73   383.2  723.84   396.1  719.98   403.1  719.17
   411.1  720.07     427  722.38   474.6  722.46   494.5  726.47   546.2  723.94
   562.1  726.76     578  734.99   593.9  746.59   613.7  755.74   669.4  769.98
     725  796.68   752.8  812.71   816.4  859.26   832.3  872.55   852.2  885.74
#Mann= 3 , 0 , 0
       0      .1       0   396.1    .045       0   411.1      .1       0
Bank Sta=396.1,411.1
XS Rating Curve= 0 ,0
Exp/Cntr=0.3,0.1

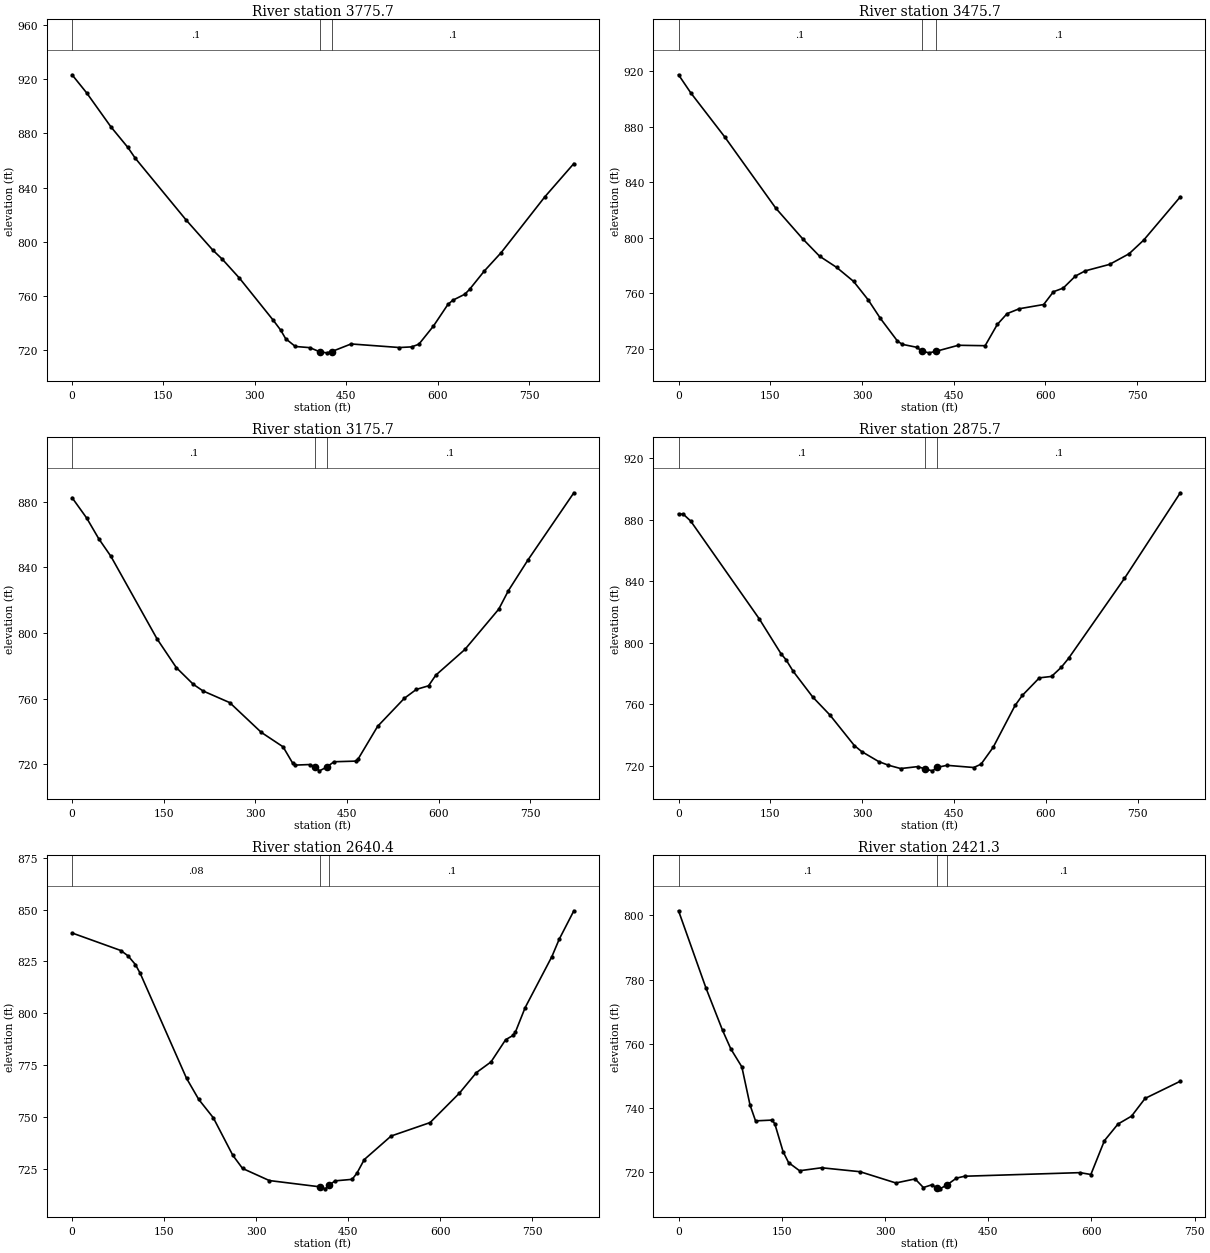
Type RM Length L Ch R = 1 ,3775.7  ,301.3,300,299.6
XS GIS Cut Line= 3
     1711493.244      413924.826     1711844.445      414144.128
     1712191.502      414360.976
#Sta/Elev= 30
       0  923.26    23.9  909.94    63.7  884.87    91.6  869.63   103.5  861.82
   187.1  816.14   230.9  793.94   246.8  787.06   274.7  773.21   330.4     742
   342.4  734.82   350.4   728.6   366.3  722.83   390.2  721.97   406.5  718.86
     418  718.14     426  719.07   457.8  724.69   537.2  722.06   557.1  722.53
     569  724.49   592.8  737.82   616.7  753.87   624.6  756.92   644.5   761.4
   652.4  765.08   676.3  778.46   704.1  792.11   775.6  833.19   823.3  857.78
#Mann= 3 , 0 , 0
       0      .1       0   406.5    .045       0     426      .1       0
Bank Sta=406.5,426
XS Rating Curve= 0 ,0
Exp/Cntr=0.3,0.1

Type RM Length L Ch R = 1 ,3475.7  ,297.8,300,300.5
XS GIS Cut Line= 3
     1711296.838      414183.824     1711658.751      414375.625
      1712011.65      414586.287
#Sta/Elev= 30
       0  917.63    19.9  904.67    75.6   872.8   159.1  821.43   202.8   799.5
   230.6  786.86   258.5   778.8   286.3  768.67   310.2  755.34   330.1     742
   357.9  725.74   365.8  723.32   389.7  721.17   397.7  718.45   409.6  717.18
   421.6  718.33   457.5  722.63   501.4  722.32   521.3  737.66   537.3  745.44
   557.2  748.97   597.1  752.01   613.1  761.23   629.1  763.86     649  772.52
     665  776.26   704.9  780.94   736.8   788.6   760.7  798.44   820.6  829.66
#Mann= 3 , 0 , 0
       0      .1       0   397.7    .045       0   421.6      .1       0
Bank Sta=397.7,421.6
XS Rating Curve= 0 ,0
Exp/Cntr=0.3,0.1

Type RM Length L Ch R = 1 ,3175.7  ,299.1,300,301
XS GIS Cut Line= 3
     1711133.912      414389.451     1711476.823      414612.341
     1711823.898      414835.129
#Sta/Elev= 30
       0  882.38    23.8  870.05    43.7  857.37    63.5  846.72     139  796.49
   170.7  778.91   198.5  768.75   214.4  764.73   258.1  757.62   309.7  739.53
   345.4  730.72   361.3  720.67   365.3   719.6   389.1  719.93   397.1  718.71
     405   716.1   416.5  718.32   428.8  721.63   464.5  722.02   468.5  723.45
   500.2   743.2   543.8  760.22   563.6  765.68   583.5  767.86   595.4  774.34
     643  789.97   698.5  814.54   714.3  825.82   746.1  844.38   821.4  885.36
#Mann= 3 , 0 , 0
       0      .1       0   397.1    .045       0   416.5      .1       0
Bank Sta=397.1,416.5
XS Rating Curve= 0 ,0
Exp/Cntr=0.3,0.1

Type RM Length L Ch R = 1 ,2875.7  ,228,235.3,240.6
XS GIS Cut Line= 3
     1710984.565      414620.791      1711319.48      414858.649
      1711651.99      415096.923
#Sta/Elev= 30
       0  883.92       8  883.53    19.9  879.14   131.6  815.65   167.5  792.74
   175.5  788.94   187.4  781.29   219.4  764.53   247.3   752.9   287.2  733.03
   299.1  729.13     327  722.59     343   720.2   362.9  718.04   390.8   719.3
   403.3  717.69   414.8  716.55   422.7  718.82   438.6  720.14   482.3  718.72
   494.2  720.88     514  731.85   549.8   759.1   561.7  765.67   589.5  777.08
   609.4  778.01   625.2  783.91   637.2  789.77   728.5   841.8   819.8  897.56
#Mann= 3 , 0 , 0
       0      .1       0   403.3    .045       0   422.7      .1       0
Bank Sta=403.3,422.7
XS Rating Curve= 0 ,0
Exp/Cntr=0.3,0.1

Type RM Length L Ch R = 1 ,2640.4  ,259.2,219.1,182.4
XS GIS Cut Line= 3
     1710914.221      414699.635     1711165.946      415021.664
     1711437.213      415327.654
#Sta/Elev= 30
       0  838.72    79.4  830.28    91.3  827.68   103.2  823.52   111.1  819.25
   186.5  768.78   206.4  758.62   230.2  749.76   261.9  731.73   277.8  725.39
   321.4  719.56   404.4  716.52   412.7  715.57   419.4  717.46   428.6  719.41
   456.4  720.14   464.3  723.17   476.2  729.67   519.9  740.99   583.4  747.46
   631.1  761.59   658.9  771.53   682.7  776.66   706.5  787.34   718.4  789.38
   722.4  790.98   738.3  802.78   781.9  827.36   793.8   835.7   817.7   849.4
#Mann= 3 , 0 , 0
       0     .08       0   404.4    .045       0   419.4      .1       0
Bank Sta=404.4,419.4
XS Rating Curve= 0 ,0
Exp/Cntr=0.3,0.1

Type RM Length L Ch R = 1 ,2421.3  ,80.6,84.1,85.5
XS GIS Cut Line= 3
     1710669.852      415343.365     1711160.737      415050.397
     1711267.508      415166.282
#Sta/Elev= 30
       0  801.46      40   777.3      64  764.18      76   758.4      92   752.8
   103.9  740.91   111.9  735.97   135.9  736.21   139.9  735.06   151.9   726.4
   159.9  722.96   175.9  720.42   207.9  721.35   263.8  720.12   315.8  716.61
   343.8  717.87   355.8  715.19   367.8  716.02   375.3  715.08   379.8  714.78
   390.3  716.03   403.8  718.12   415.8  718.71   583.5  719.83   599.2  719.25
   618.9   729.8   638.6  734.98   658.3  737.44     678  742.97   729.2  748.33
#Mann= 3 , 0 , 0
       0      .1       0   375.3    .045       0   390.3      .1       0
Bank Sta=375.3,390.3
XS Rating Curve= 0 ,0
Exp/Cntr=0.3,0.1

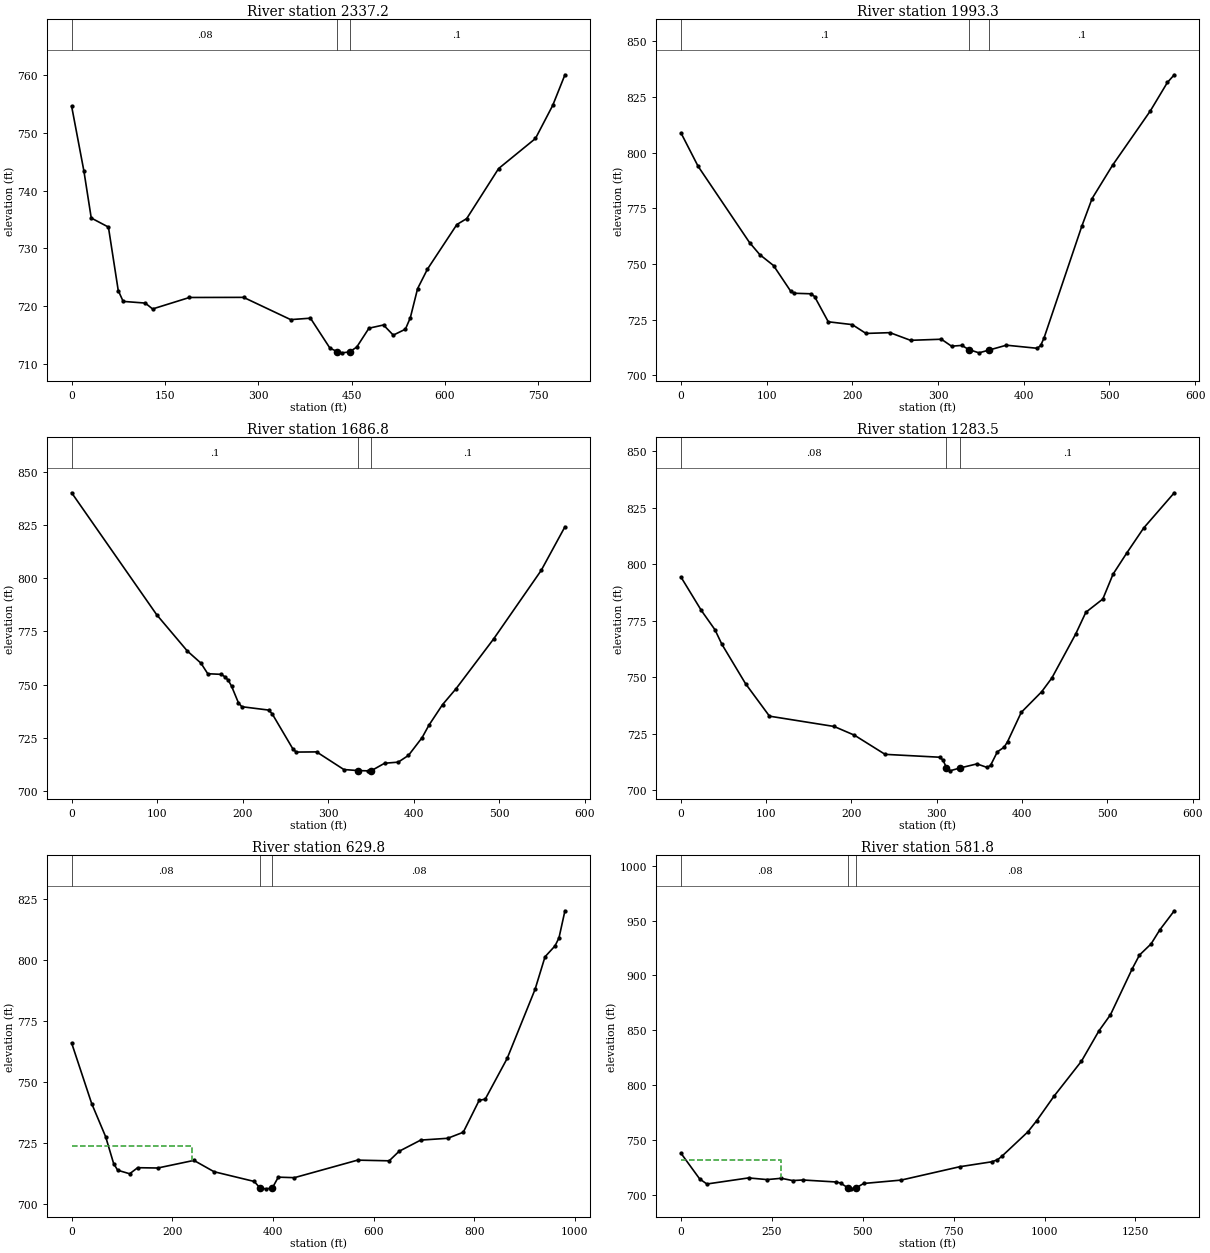
Type RM Length L Ch R = 1 ,2337.2  ,329.9,343.9,357.6
XS GIS Cut Line= 6
     1710771.414      415476.178      1710928.75      415465.763
     1710927.664      415355.084     1710983.654      415249.615
     1711180.269      415099.876     1711283.133      415219.668
#Sta/Elev= 30
       0  754.63    19.7  743.41    31.5  735.26    59.1  733.69    74.9  722.68
    82.8   720.8   118.3  720.51   130.1  719.49   189.3  721.48   276.3   721.5
     352  717.64   383.8  717.89   415.2  712.68   426.9   712.1   434.7  711.88
   446.6  712.04   458.2  712.88   477.8  716.15   501.2  716.71   516.9  714.95
   536.4  715.98   544.3  717.97     556  723.02   571.8  726.39   619.1  734.13
   634.9  735.16   686.2  743.84   745.4  749.05   773.1  754.78   792.8   760.1
#Mann= 3 , 0 , 0
       0     .08       0   426.9    .045       0   446.6      .1       0
Bank Sta=426.9,446.6
XS Rating Curve= 0 ,0
Exp/Cntr=0.3,0.1

Type RM Length L Ch R = 1 ,1993.3  ,307.9,306.5,304.6
XS GIS Cut Line= 2
      1710690.36      415563.309     1711265.881      415547.684
#Sta/Elev= 30
       0  808.89      20   793.9      80  759.68      92  754.24     108  749.36
   127.9  737.92   131.9  736.92   151.9  736.67   155.9  735.45   171.9  724.11
   199.9  722.84   215.9  718.88   243.9  719.23   267.9  715.79   303.9  716.28
   315.8  713.15   327.8  713.51   335.8  711.66   347.8  710.17   359.1  711.37
   379.8   713.6   415.8  712.21   419.8  713.48   423.8  716.95   467.8  767.02
   479.8  779.43   503.8  794.45   547.8  818.79   567.7  831.55   575.7  834.98
#Mann= 3 , 0 , 0
       0      .1       0   335.8    .045       0   359.1      .1       0
Bank Sta=335.8,359.1
XS Rating Curve= 0 ,0
Exp/Cntr=0.3,0.1

Type RM Length L Ch R = 1 ,1686.8  ,415.4,403.3,390.8
XS GIS Cut Line= 2
     1710666.922      415881.017     1711242.443      415839.351
#Sta/Elev= 30
       0  840.07    99.5  782.84   135.3  765.83   151.2  760.16   159.2  755.17
   175.1  754.88   179.1  753.77   183.1  752.16     187  749.38     195  741.61
     199   739.7   230.8   738.1   234.8   736.2   258.7  719.94   262.6  718.41
   286.5   718.5   318.4  710.22   335.2  709.73   346.2  709.61   350.2  709.61
   366.1  713.18     382  713.69     394  716.87   409.9  725.18   417.8  730.96
   433.8  740.67   449.7  748.18   493.5  771.45   549.2  803.64     577  824.12
#Mann= 3 , 0 , 0
       0      .1       0   335.2    .045       0   350.2      .1       0
Bank Sta=335.2,350.2
XS Rating Curve= 0 ,0
Exp/Cntr=0.3,0.1

Type RM Length L Ch R = 1 ,1283.5  ,663.9,653.7,642.6
XS GIS Cut Line= 2
     1710807.547      416427.892     1711271.089      416081.538
#Sta/Elev= 30
       0  794.41    23.9  779.62    39.9  771.07    47.9  764.71    75.8  747.18
   103.8  732.84   179.6  728.28   203.5  724.41   239.4  715.94   303.3  714.67
   307.3  713.43   311.3  710.09   315.3  708.64   327.8  709.96   347.2  711.71
   359.2  710.12   363.2  711.13   371.1  717.05   379.1  719.13   383.1  721.58
   399.1  734.51     423  743.62     435  749.72   462.9  769.15   474.9  778.82
   494.8  784.69   506.8   795.7   522.8  805.01   542.7  816.11   578.6  831.71
#Mann= 3 , 0 , 0
       0     .08       0   311.3    .045       0   327.8      .1       0
Bank Sta=311.3,327.8
XS Rating Curve= 0 ,0
Exp/Cntr=0.3,0.1

Type RM Length L Ch R = 1 ,629.8   ,44.8,48.1,51.3
XS GIS Cut Line= 6
     1711391.206      416732.688     1711521.414      416769.147
     1711656.831      416493.105     1711755.789      416342.063
     1711733.654      416287.376     1711563.624       416042.91
#Sta/Elev= 30
       0  765.86    39.8   741.1    67.6   727.5    83.5   716.5    91.5   713.8
   115.3  712.35   131.2  714.83   171.2  714.71     243  717.82     283  713.19
   362.8  709.21   374.8  706.44   386.8  706.18   398.8  706.53   410.7  710.96
   442.7  710.75   568.3  717.93   631.1  717.65   650.8  721.55   693.7  726.13
   747.3  726.87   778.3  729.34     810  742.44   821.9  742.87   865.5  759.54
     921  787.84   940.8  801.17   960.6  805.61   968.5  808.88   980.4     820
#Mann= 3 , 0 , 0
       0     .08       0   374.8    .045       0   398.8     .08       0
#XS Ineff= 2 , 0
          238.55  723.71
Permanent Ineff=
       F       F
Bank Sta=374.8,398.8
XS Rating Curve= 0 ,0
Exp/Cntr=0.3,0.1

Type RM Length L Ch R = 1 ,581.8   ,445.2,466.3,492
XS GIS Cut Line= 6
     1711395.112      416847.272      1711543.55      416872.011
     1711591.727      416710.553      1711643.81      416611.595
       1711824.8      416329.043     1712414.318      416303.326
#Sta/Elev= 30
       0  738.08    51.5  714.65    71.3  710.06   185.8  715.59   236.7  714.08
   275.9  715.25   307.2  713.18     335  713.71   426.8  711.89   438.8  710.95
   459.3  706.52   466.6  705.65   482.5  706.66   502.3  710.53   605.5  713.61
   766.6  725.78   854.3  730.26   870.3   732.1   882.2   735.2     954  757.51
   977.9  767.51  1025.8  789.96  1101.5  821.94  1149.4  849.47  1181.3  864.24
  1241.1  906.08    1261  918.55  1292.9   928.7  1316.8  941.44  1356.7  958.87
#Mann= 3 , 0 , 0
       0     .08       0   459.3    .045       0   482.5     .08       0
#XS Ineff= 2 , 0
           276.2  731.79
Permanent Ineff=
       F       F
Bank Sta=459.3,482.5
XS Rating Curve= 0 ,0
Exp/Cntr=0.3,0.1

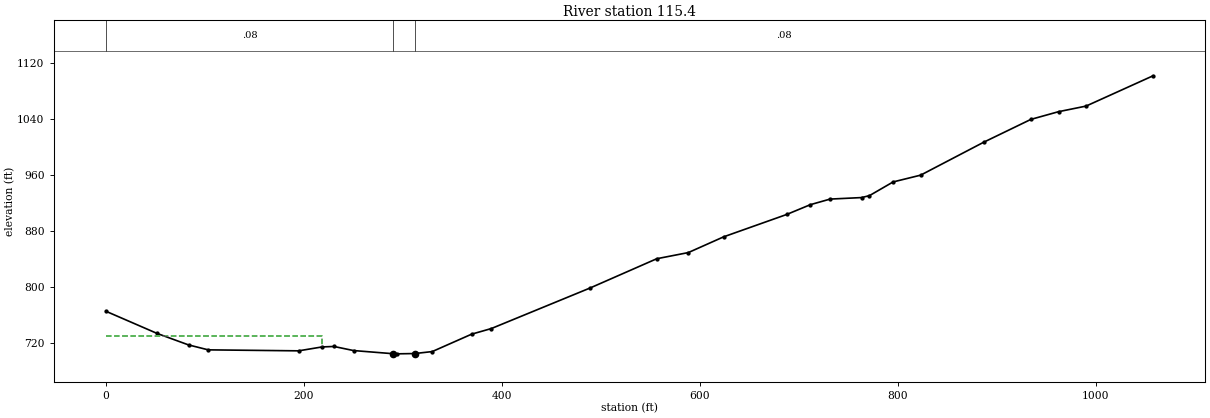
Type RM Length L Ch R = 1 ,115.4   ,86.5,115.4,138.2
XS GIS Cut Line= 3
     1711331.419      416871.903     1711620.047      416926.156
     1712355.724      417132.319
#Sta/Elev= 30
       0  765.35    51.6  733.68    83.3  717.29   103.2  710.22   194.5  708.81
   218.3  714.42   230.2  715.06     250  709.22   289.7  704.73   293.7  704.52
   311.8  704.94   329.5  707.76   369.3  732.67   389.2  740.71   488.7  798.57
   556.3  840.59   588.2   849.4     624  871.99   687.6  903.94   711.5  917.94
   731.4  925.93   763.2   928.1   771.2  930.89   795.1  950.48   822.9  960.18
   886.6 1007.29   934.3 1039.98   962.2 1050.98     990 1058.99  1057.7 1102.36
#Mann= 3 , 0 , 0
       0     .08       0   289.7    .045       0   311.8     .08       0
#XS Ineff= 2 , 0
          218.43  729.76
Permanent Ineff=
       F       F
Bank Sta=289.7,311.8
XS Rating Curve= 0 ,0
Exp/Cntr=0.3,0.1

Chan Stop Cuts=-1
Use User Specified Reach Order=0
Composite Channel Slope=5